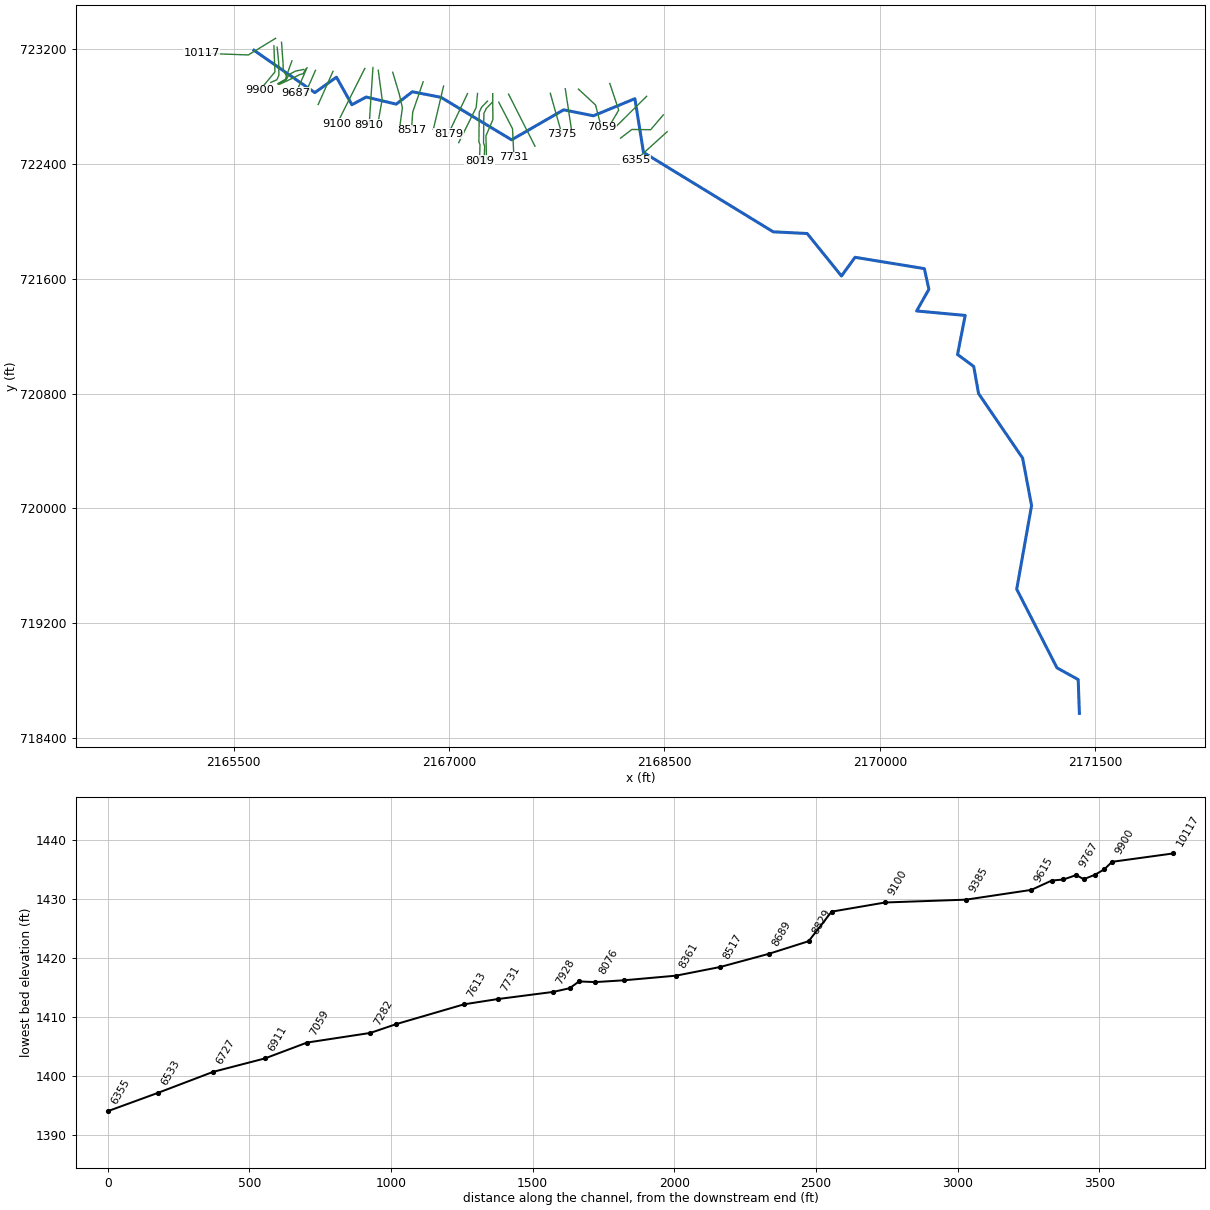
--- SPRUCEFK.prj (project) ---

Proj Title=SPRUCEFK
Current Plan=p01
Default Exp/Contr=0,0
English Units
Geom File=g01
Flow File=f01
Plan File=p01
BEGIN DESCRIPTION:
---------- MODELED AS PART OF WVEMD CTP PROGRAM, 2023----------
Stream Name: Spruce Fork
Flood Zone:  AFH
Upshur County, WV
HEC-RAS Version: RAS 6.3
Vertical Datum: NAVD88
Projection: NAD 1983 StatePlane West Virginia S FIPS 4702 (US Feet)
Terrain: 1-meter LIDAR (FEMA Region III 3DEP collected 2016-2018)
Land Use: 2019 NLCD
Hydrologic Method:
WV 2010 Regional Regression Equations
Additional Model Notes:
None
END DESCRIPTION:
DSS Export Rating Curves= 0
DSS Export Rating Curve Sorted= 0
DSS Export Volume Flow Curves= 0
DXF OffsetX= 0
DXF OffsetY= 0
DXF ScaleX= 0
DXF ScaleY= 0

--- SPRUCEFK.p01 (plan) ---

Plan Title=Floodplain
Program Version=6.31
Short Identifier=Floodplain
Geom File=g01
Flow File=f01
Subcritical Flow
K Sum by GR= 0
Std Step Tol= 0.01
Critical Tol= 0.01
Num of Std Step Trials= 20
Max Error Tol= 0.3
Flow Tol Ratio= 0.001
Split Flow NTrial= 30
Split Flow Tol= 0.02
Split Flow Ratio= 0.02
Log Output Level= 0
Friction Slope Method= 1
Unsteady Friction Slope Method= 2
Unsteady Bridges Friction Slope Method= 1
Parabolic Critical Depth
Global Vel Dist= 0 , 0 , 0
Global Log Level= 0
CheckData=True
Encroach Param=-1 ,0,0, 0
Mapping Interval=1HOUR
Computation Time Step Use Courant=        0
Computation Time Step Use Time Series=    0
Computation Time Step Count To Double=0
Computation Time Step Max Doubling=0
Computation Time Step Max Halving=0
Computation Time Step Residence Courant=0
Run HTab= 0
Run UNet= 0
Run Sediment= 0
Run PostProcess= 0
Run WQNet= 0
Run RASMapper=-1
UNET Theta= 0
UNET Theta Warmup= 0
UNET ZTol= 0
UNET ZSATol= 0
UNET MxIter= 0
UNET Max Iter WO Improvement= 0
UNET MaxInSteps= 0
UNET DtIC= 0
UNET DtMin= 0
UNET MaxCRTS= 0
UNET WFStab= 0
UNET SFStab= 0
UNET WFX= 1
UNET SFX= 1
UNET Gravity=32.17405
UNET 1D Methodology=Finite Difference
UNET DSS MLevel= 1
UNET Pardiso=0
UNET DZMax Abort= 0
UNET Use Existing IB Tables= 0
UNET Froude Reduction=False
UNET Froude Limit= 0
UNET Froude Power= 0
UNET D1 Cores= 0
UNET WindReference=Eulerian
UNET WindDragFormulation=Hsu (1988)
UNET D2 Coriolis=0
UNET D2 Cores= 0
UNET D2 Theta= 1
UNET D2 Theta Warmup= 1
UNET D2 Z Tol= 0.01
UNET D2 Volume Tol= 0.01
UNET D2 Max Iterations= 20
UNET D2 Equation= 0
UNET D2 RampUpFraction=0.1
UNET D2 TimeSlices= 1
UNET D2 Turbulence Formulation=Non-Conservative (original)
UNET D2 Eddy Viscosity=0.3
UNET D2 Transverse Eddy Viscosity=0.1
UNET D2 Smagorinsky Mixing=0
UNET D2 BCVolumeCheck=0
UNET D2 Cores=0
UNET D2 SolverType=PARDISO (Direct)
UNET D2 Minimum Iterations= 3
UNET D2 Maximum Iterations= 30
UNET D2 Restart Number= 10
UNET D2 Relaxation Coeff=1.3
UNET D2 SOR Precondition Iterations= 10
UNET D2 ILUT Maximum Fill= 8
UNET D2 ILUT Tolerance=1E-08
UNET D2 Convergence Tolerance=0.00001
UNET D1D2 MaxIter= 0
UNET D1D2 ZTol=0.01
UNET D1D2 QTol=0.1
UNET D1D2 MinQTol=1
Write IC File= 0
Write IC File at Fixed DateTime=0
Write IC File at Sim End=0
Echo Input=False
Echo Parameters=False
Echo Output=False
Write Detailed= 0
HDF Write Warmup=0
HDF Write Time Slices=0
HDF Flush=0
HDF Compression= 1
HDF Chunk Size= 1
HDF Spatial Parts= 1
HDF Use Max Rows=0
HDF Fixed Rows= 1
Calibration Method= 0
Calibration Iterations= 20
Calibration Max Change=0.05
Calibration Tolerance=0.2
Calibration Maximum=1.5
Calibration Minimum=0.5
Calibration Optimization Method= 1
WQ AD Non Conservative
WQ ULTIMATE=-1
WQ Max Comp Step=1HOUR
WQ Output Interval=15MIN
WQ Output Selected Increments= 0
WQ Create Restart=0
WQ Fixed Restart=0
WQ System Summary=0
WQ Write To DSS=0
Sorting and Armoring Iterations= 10
XS Update Threshold= 0.02
Bed Roughness Predictor= 0
Hydraulics Update Threshold= 0.02
Energy Slope Method= 1
Volume Change Method= 1
Sediment Retention Method= 0
Sediment TS Multiplier= 1
Warm Up Method= 0
XS Weighting Method= 0
Number of US Weighted Cross Sections= 1
Number of DS Weighted Cross Sections= 1
Upstream XS Weight=0
Main XS Weight=1
Downstream XS Weight=0
Number of DS XS's Weighted with US Boundary= 1
Upstream Boundary Weight= 1
Weight of XSs Associated with US Boundary= 0
Number of US XS's Weighted with DS Boundary= 1
Downstream Boundary Weight= 0.5
Weight of XSs Associated with DS Boundary= 0.5
Percentile Method= 0
Sediment Output Level= 3
Mass or Volume Output= 0
Output Increment Type= 1
Profile and TS Output Increment= 1
Transport Output Increment 1
XS Output Flag= 0
XS Output Increment= 10
Read HDF5 Sediment Hotstart= 0
Sediment Hotstart Type= 0
Write Gradation File= 0
Read Gradation Hotstart= 0
Write HDF5 File= 1
Write Binary Output= 1
Write DSS Sediment File= 0
DSS Sediment Output Type= 1
SV Curve= 0
Specific Gage Flag= 0
Subcell Erosion Methods= 0
Subcell Deposition Methods= 0
Advection Scheme= 1
Matrix Solver= 0
Implicit Weighting Factor= 1
Maximum Outer Loop Convergence Iterations= 5
Convergence Maximum Absolute= 0.001
Convergence RMSE= 0.0001
Grain Fractions Max Abs Error= 0.001
Max Subgrid Regions= 1
Max Subgrid Length Scale= 3.402823E+38
Initial Layer Thickness= 3.402823E+38
Min Layer Thickness= 3.402823E+38
Max Layer Thickness= 3.402823E+38
Number of Layers= 5

--- SPRUCEFK.f01 (steady flow) ---

Flow Title=Flows
Program Version=6.31
Number of Profiles= 1
Profile Names=01pct
River Rch & RM=SPRUCEFK,Main,10117
     791
River Rch & RM=SPRUCEFK,Main,5537
     896
River Rch & RM=SPRUCEFK,Main,3295
     999
Boundary for River Rch & Prof#=SPRUCEFK,Main            , 1
Up Type= 0
Dn Type= 3
Dn Slope=0.02007
DSS Import GetInterval= 0
DSS Import GetPeak= 0
DSS Import FillOption= 0

--- SPRUCEFK.g01 (geometry) ---

Geom Title=Geometry
Program Version=6.31

River Reach=SPRUCEFK        ,Main
Reach XY= 30
     2165641.326       723193.32     2166065.021      722897.971
     2166215.886      723005.654     2166323.369      722813.466
     2166422.697      722867.265     2166631.911      722817.702
     2166744.517      722904.066     2166943.486      722865.291
      2167435.66      722569.054     2167797.886      722778.039
     2168005.412      722736.574     2168294.466       722855.79
     2168354.217      722481.316     2169257.751      721927.818
      2169494.38      721915.942     2169733.241       721619.82
     2169827.847      721750.224     2170310.662      721671.129
     2170342.284      721527.274     2170256.806      721376.122
     2170595.023      721345.102     2170541.711      721072.817
     2170654.345      720989.658     2170688.084      720800.532
     2170995.052      720350.511     2171057.293      720019.419
     2170953.844      719436.733     2171234.256      718888.671
     2171382.089      718806.829     2171390.416       718571.23

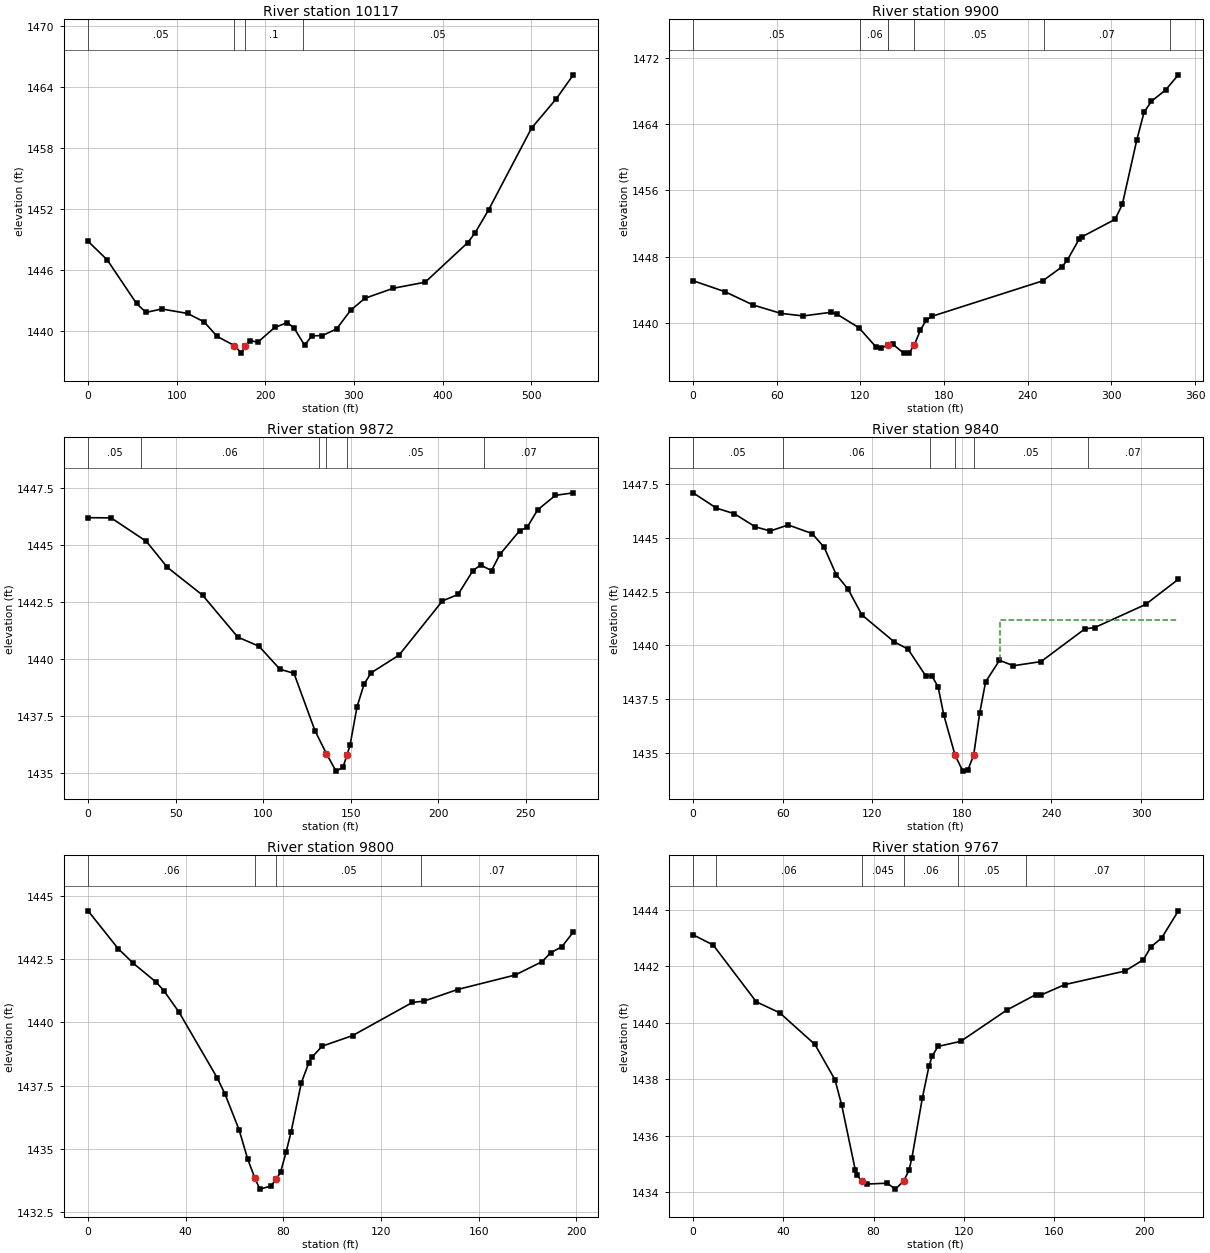
Type RM Length L Ch R = 1 ,10117   ,194.1,216.7,218.6
XS GIS Cut Line= 3
2165792.06493549723276.4285238452165601.98796404723160.689542062
2165277.14924837723172.290924764
#Sta/Elev= 30
       0 1448.81    21.6 1446.98    54.7 1442.68    65.4  1441.8    83.2 1442.14
   112.3  1441.7     131 1440.87   145.6 1439.44165.2009 1438.53   173.1 1437.79
177.51081438.525   182.8    1439   191.9 1438.89   210.6 1440.32   224.8 1440.79
   232.4 1440.28   244.4 1438.56   252.4 1439.49   264.4 1439.52   280.4 1440.17
   296.4 1442.02   312.4 1443.19   344.4 1444.18   380.5 1444.78   428.5 1448.68
   436.5  1449.6   452.2 1451.93   500.5 1459.96   528.5 1462.86   547.6 1465.21
#Mann= 4 ,-1,0
       0     .05       0165.2009    .045       0177.5108      .1       0
  242.54     .05       0
Bank Sta=165.2009,177.5108
XS Rating Curve= 0 ,0
Exp/Cntr(USF)=0,0
Exp/Cntr=0.3,0.1

Type RM Length L Ch R = 1 ,9900    ,28,27.7,27.4
XS GIS Cut Line= 3
2165780.17613675723224.0255974252165787.33312748723042.416957586
2165681.48468897722914.184536817
#Sta/Elev= 30
       0  1445.1    22.9 1443.77    42.9 1442.18    62.9 1441.16    78.9 1440.85
    98.9 1441.29   102.9 1441.09   118.9 1439.43   130.9 1437.15     135 1436.99
   140.11437.358     143 1437.46     151 1436.36     155 1436.42   158.51437.293
     163 1439.13     167  1440.3     171 1440.79   250.8 1445.09   264.4 1446.76
   268.4  1447.6   276.7 1450.08   278.6 1450.38   302.6 1452.51   307.8 1454.31
   318.2  1462.1   323.4 1465.44   328.6 1466.75     339 1468.16     348 1469.96
#Mann= 7 ,-1,0
       0     .05       0     120     .06       0     140     .05       0
   140.1    .045       0   158.5     .05       0  251.75     .07       0
  341.75     .05       0
Bank Sta=140.1,158.5
XS Rating Curve= 0 ,0
Exp/Cntr(USF)=0,0
Exp/Cntr=0.3,0.1

Type RM Length L Ch R = 1 ,9872    ,32.8,32.1,32.1
XS GIS Cut Line= 5
2165802.74857919723214.2705737882165813.03675337 723112.73076777
2165814.82600105723018.7952644052165800.51201958 722987.48342995
2165757.57007519722969.143641197
#Sta/Elev= 30
       0 1446.19    13.2 1446.18    33.3 1445.15    45.3 1444.01    65.4 1442.79
    85.5 1440.95    97.6 1440.55   109.6 1439.54   117.6 1439.36   129.6 1436.84
   136.1 1435.84   141.6 1435.07   145.6 1435.24   147.9 1435.79   149.6  1436.2
   153.6 1437.89   157.6 1438.88   161.6 1439.38   177.6 1440.16   202.4 1442.54
   211.3 1442.82   219.8 1443.87   224.2 1444.11   230.4 1443.87   235.2 1444.58
   246.5 1445.62   250.7 1445.76   256.7 1446.53   266.9 1447.17   277.1 1447.28
#Mann= 6 ,-1,0
       0     .05       0      30     .06       0  132.06     .05       0
   136.1    .045       0   147.9     .05       0  226.01     .07       0
Bank Sta=136.1,147.9
XS Rating Curve= 0 ,0
Exp/Cntr(USF)=0,0
Exp/Cntr=0.3,0.1

Type RM Length L Ch R = 1 ,9840    ,44.7,40.1,35.7
XS GIS Cut Line= 6
 2165833.1657898723248.713591688 2165843.9012759723100.206033988
2165845.24321166723053.238282305 2165867.6088077723014.769457118
2165862.68837657722991.509237237  2165809.458258722961.986650465
#Sta/Elev= 30
       0 1447.08    15.6 1446.37    27.6 1446.11    41.7  1445.5    51.7 1445.31
    63.7 1445.59    79.7 1445.19    87.8 1444.55    95.8 1443.29   103.8 1442.61
     113 1441.42   134.6 1440.17   143.9 1439.83   155.9 1438.58   159.9 1438.59
   164.1 1438.08   167.9 1436.77   175.4 1434.92   180.6 1434.17   183.9  1434.2
   187.9 1434.91   191.9 1436.85   195.9 1438.31   205.2 1439.31   214.5 1439.06
     233 1439.25   262.4 1440.77     269 1440.83     303  1441.9     325 1443.07
#Mann= 6 ,-1,0
       0     .05       0      60     .06       0   158.9     .05       0
   175.4    .045       0   187.9     .05       0  264.15     .07       0
#XS Ineff= 2 , 0
                          205.46          1441.2
Permanent Ineff=
       F       F
Bank Sta=175.4,187.9
XS Rating Curve= 0 ,0
Exp/Cntr(USF)=0,0
Exp/Cntr=0.3,0.1

Type RM Length L Ch R = 1 ,9800    ,32.9,26.4,17.5
XS GIS Cut Line= 4
2165905.63032097723119.4404465812165871.18730307723023.715695533
2165864.03031233722989.7199895542165809.90556992722958.855467019
#Sta/Elev= 30
       0 1444.41    12.3 1442.92    18.5 1442.34    27.9 1441.59      31 1441.26
    37.3  1440.4    52.9 1437.81    56.1 1437.17    61.9 1435.75    65.4  1434.6
    68.41433.831    70.4 1433.41    74.8 1433.53    77.11433.792    78.9 1434.09
    81.1 1434.86    83.2 1435.68    87.4 1437.62    90.4 1438.39    91.7 1438.62
    95.9 1439.06   108.4 1439.48   132.9 1440.79   137.6 1440.84   151.4  1441.3
   174.9 1441.87     186  1442.4   189.5 1442.75   194.1 1442.99   198.8 1443.57
#Mann= 4 ,-1,0
       0     .06       0    68.4    .045       0    77.1     .05       0
  136.47     .07       0
Bank Sta=68.4,77.1
XS Rating Curve= 0 ,0
Exp/Cntr(USF)=0,0
Exp/Cntr=0.3,0.1

Type RM Length L Ch R = 1 ,9767    ,46.3,45.1,44.6
XS GIS Cut Line= 5
2165986.98760033 723059.602098262165931.85663404723048.488472812
2165886.32120442723025.1323352492165866.26687194722988.825365712
2165811.24750568722957.513531257
#Sta/Elev= 30
       0 1443.11     8.9 1442.75      28 1440.74    38.4 1440.35      54 1439.23
    62.9 1437.98    65.9 1437.07    71.9 1434.78    72.5 1434.62    74.7  1434.4
      77 1434.29      86 1434.32    89.7 1434.11   93.37  1434.4    95.7 1434.78
      97 1435.22   101.6 1437.33   104.6 1438.48     106 1438.82   108.5 1439.16
   118.6 1439.34   139.1 1440.45   151.8 1440.99   154.2 1440.98   164.8 1441.35
   191.5 1441.83   199.6 1442.23   202.9 1442.68   207.7    1443   215.1 1443.96
#Mann= 6 ,-1,0
       0     .05       0      10     .06       0    74.7    .045       0
   93.37     .06       0  117.42     .05       0  147.42     .07       0
Bank Sta=74.7,93.37
XS Rating Curve= 0 ,0
Exp/Cntr(USF)=0,0
Exp/Cntr=0.3,0.1

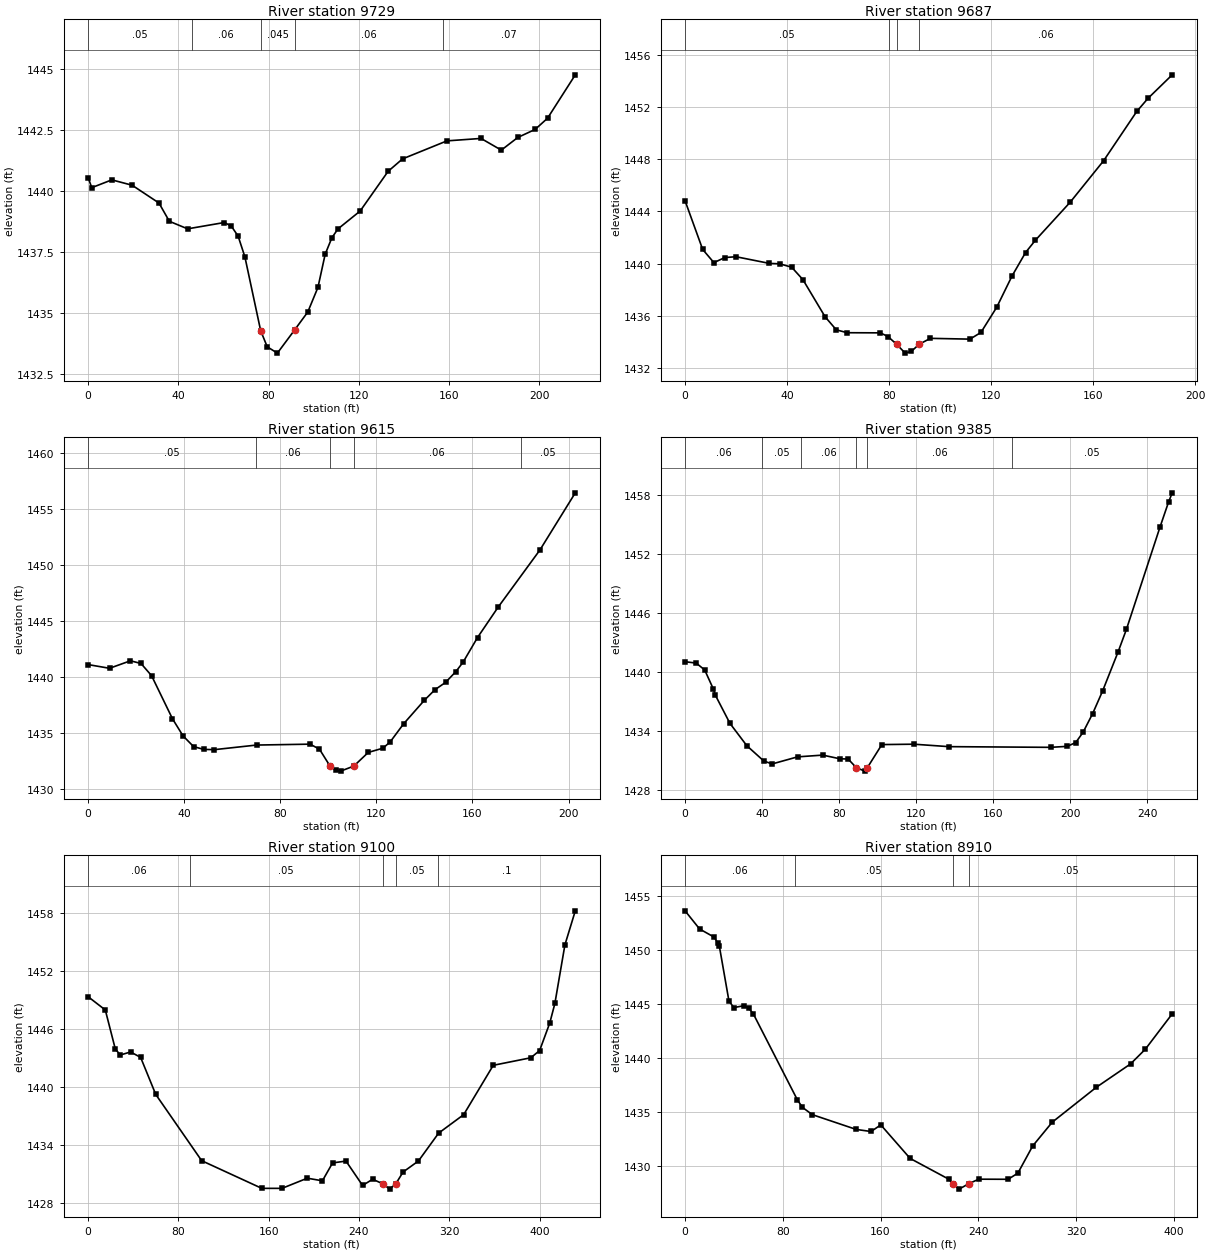
Type RM Length L Ch R = 1 ,9729    ,33.8,41.8,52.1
XS GIS Cut Line= 5
2166001.00716274723062.5821313172165984.78961254723030.426633429
2165959.75506338723023.715695533 2165910.5507521722998.666227969
2165821.08836794722956.618907415
#Sta/Elev= 30
       0 1440.56     1.6 1440.15    10.5 1440.47    19.5 1440.25    31.4 1439.52
      36 1438.77    44.1 1438.46    60.4 1438.72    63.5 1438.57    66.5 1438.16
    69.5 1437.31    76.51434.279    79.4 1433.62    83.9 1433.36    91.51434.305
    97.4 1435.05   101.9 1436.06   105.1 1437.42   108.1  1438.1   110.8 1438.46
   120.6 1439.19     133 1440.82   139.4 1441.33   159.1 1442.07   174.2 1442.17
   183.2 1441.69   190.5 1442.21   198.2 1442.54   203.7    1443     216 1444.78
#Mann= 5 ,-1,0
       0     .05       0   46.01     .06       0    76.5    .045       0
    91.5     .06       0  157.15     .07       0
Bank Sta=76.5,91.5
XS Rating Curve= 0 ,0
Exp/Cntr(USF)=0,0
Exp/Cntr=0.3,0.1

Type RM Length L Ch R = 1 ,9687    ,71.4,71.6,69.2
XS GIS Cut Line= 2
2166010.73025991723071.4898646532165934.22006668722896.501204893
#Sta/Elev= 30
       0 1444.82     6.9  1441.1    11.3 1440.09    15.6 1440.48      20 1440.54
    33.1 1440.03    37.1    1440    41.8 1439.74    46.2 1438.79    54.9 1435.95
    59.3 1434.95    63.6 1434.73    76.6 1434.72    79.6 1434.43    82.91433.854
    86.3 1433.17    88.7  1433.3    91.8 1433.85    96.2  1434.3   111.7 1434.24
     116 1434.75   122.2 1436.68   128.2 1439.07   133.5 1440.86   137.3 1441.79
     151 1444.71   164.1 1447.88   177.1 1451.65   181.5 1452.65     191 1454.45
#Mann= 4 ,-1,0
       0     .05       0      80     .06       0    82.9    .045       0
    91.8     .06       0
Bank Sta=82.9,91.8
XS Rating Curve= 0 ,0
Exp/Cntr(USF)=0,0
Exp/Cntr=0.3,0.1

Type RM Length L Ch R = 1 ,9615    ,228.8,230.5,225.5
XS GIS Cut Line= 2
2166069.81733982723053.3092246782165988.00445994722867.715191599
#Sta/Elev= 30
       0 1441.11     8.9 1440.78    17.6 1441.45      22 1441.21    26.4 1440.12
    35.1 1436.27    39.5 1434.74    43.9 1433.78    48.2 1433.53    52.6 1433.51
    70.1 1433.92    92.4    1434    96.3 1433.55   100.7 1432.04   103.2 1431.66
   105.1 1431.59   110.6 1432.04   116.6 1433.26   122.7 1433.64   125.7 1434.19
   131.3 1435.81     140 1437.93   144.4 1438.87   148.8 1439.52   153.1 1440.49
   156.1 1441.33   162.1 1443.53   170.6 1446.22   188.1 1451.36   202.8 1456.46
#Mann= 5 ,-1,0
       0     .05       0      70     .06       0   100.7    .045       0
   110.6     .06       0     180     .05       0
Bank Sta=100.7,110.6
XS Rating Curve= 0 ,0
Exp/Cntr(USF)=0,0
Exp/Cntr=0.3,0.1

Type RM Length L Ch R = 1 ,9385    ,283.6,285.1,282.6
XS GIS Cut Line= 2
2166191.77913299723046.4914846872166088.75550646722815.445851671
#Sta/Elev= 30
       0 1441.06     5.8 1440.92    10.2 1440.22    14.6 1438.32    15.8 1437.63
    23.3 1434.79    32.1 1432.51    40.9 1430.96    45.2 1430.66    58.4 1431.38
    71.5 1431.56    80.3 1431.19    84.7 1431.16      89 1430.27    93.4 1429.93
    94.6 1430.26   102.2 1432.63   118.8 1432.67     137 1432.42   189.8 1432.35
   198.5 1432.45   202.9 1432.84   206.7 1433.88   211.7 1435.79   216.8 1438.06
   224.9 1442.06   229.2 1444.34   246.7 1454.78   251.1  1457.3     253 1458.24
#Mann= 6 ,-1,0
       0     .06       0      40     .05       0      60     .06       0
      89    .045       0    94.6     .06       0     170     .05       0
Bank Sta=89,94.6
XS Rating Curve= 0 ,0
Exp/Cntr(USF)=0,0
Exp/Cntr=0.3,0.1

Type RM Length L Ch R = 1 ,9100    ,183.6,189.3,191.4
XS GIS Cut Line= 2
2166413.32025372723066.7427582892166219.54895465722680.961717422
#Sta/Elev= 30
       0 1449.34    15.2 1447.97    24.1 1443.92    28.6 1443.32    37.6 1443.63
    46.5 1443.07    59.9 1439.24   100.6 1432.39   153.9 1429.53   171.8 1429.53
   194.2 1430.58   207.6 1430.31   216.6 1432.16   228.5 1432.35   243.2 1429.83
   252.1 1430.47   261.2    1430   267.2 1429.45  272.641430.001   279.1 1431.22
   292.7 1432.36   310.6 1435.24   332.8 1437.15     359 1442.25   392.3 1443.03
   400.1 1443.78   409.1 1446.63   413.6 1448.64   422.5  1454.7   431.7 1458.22
#Mann= 5 ,-1,0
       0     .06       0      90     .05       0   261.2    .045       0
  272.64     .05       0     310      .1       0
Bank Sta=261.2,272.64
XS Rating Curve= 0 ,0
Exp/Cntr(USF)=0,0
Exp/Cntr=0.3,0.1

Type RM Length L Ch R = 1 ,8910    ,80.7,81,79.7
XS GIS Cut Line= 2
2166469.93859663723073.0247776572166443.88681343722675.142997866
#Sta/Elev= 30
       0 1453.63    11.9 1451.95    23.9 1451.19      27 1450.61      28  1450.4
    35.9  1445.3    39.9 1444.68    47.9 1444.85      52 1444.65      56 1444.07
      92 1436.13    96.1 1435.45   104.1 1434.78   140.1 1433.41   152.2 1433.22
   160.2 1433.83   184.2 1430.73     216  1428.8  219.021428.384   224.3 1427.89
   232.3  1428.4   240.4 1428.81   264.4  1428.8   272.4 1429.37   284.5 1431.88
   300.5 1434.08   336.6 1437.31   364.6 1439.47   376.7 1440.83   398.7  1444.1
#Mann= 4 ,-1,0
       0     .06       0      90     .05       0  219.02    .045       0
   232.3     .05       0
Bank Sta=219.02,232.3
XS Rating Curve= 0 ,0
Exp/Cntr(USF)=0,0
Exp/Cntr=0.3,0.1

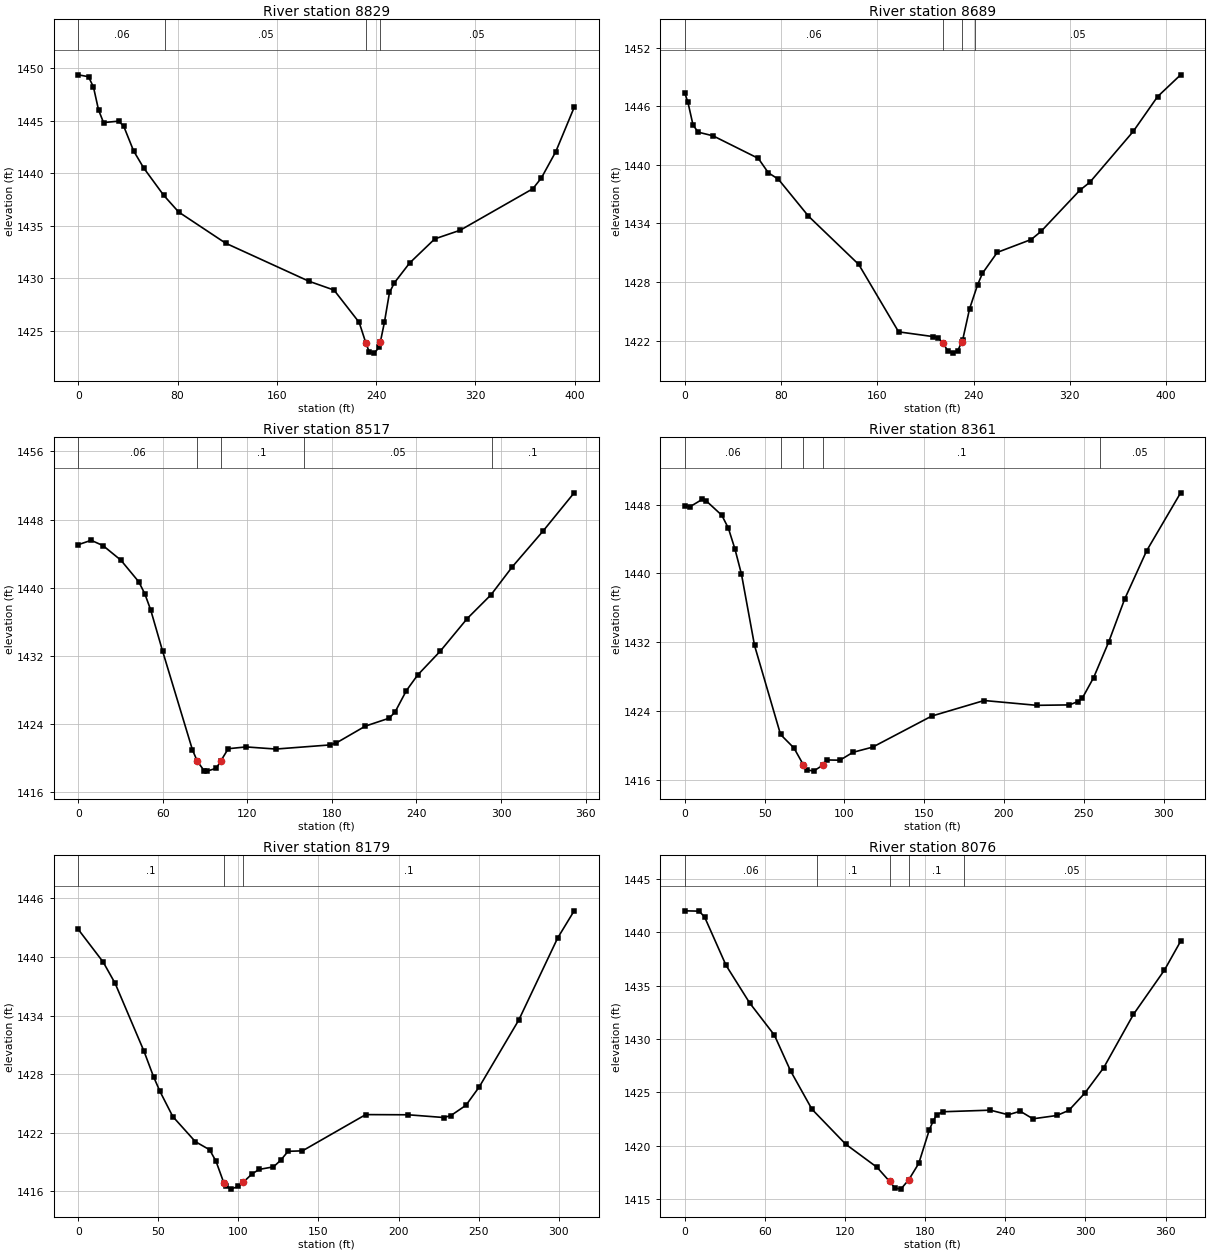
Type RM Length L Ch R = 1 ,8829    ,133.1,140.7,147.2
XS GIS Cut Line= 3
2166506.91022589723053.3092246782166534.18118585 722850.29207829
 2166500.0924859722658.637831887
#Sta/Elev= 30
       0 1449.35     8.2 1449.17    12.2 1448.18    16.3    1446    20.3 1444.81
    32.4 1444.94    36.5 1444.48    44.5 1442.12    52.6  1440.5    68.7  1437.9
    80.8  1436.3   118.7 1433.33   185.8 1429.71     206 1428.87   226.3 1425.79
   231.7 1423.82   234.4 1422.98   238.5 1422.87   242.5 1423.46   243.3  1423.9
   246.6 1425.79   250.7 1428.64   254.7 1429.57   266.9 1431.44   287.2 1433.74
   307.6 1434.56   366.2 1438.51   373.1 1439.54   384.7 1442.04   399.5 1446.25
#Mann= 4 ,-1,0
       0     .06       0      70     .05       0   231.7    .045       0
   243.3     .05       0
Bank Sta=231.7,243.3
XS Rating Curve= 0 ,0
Exp/Cntr(USF)=0,0
Exp/Cntr=0.3,0.1

Type RM Length L Ch R = 1 ,8689    ,174.6,171.1,160.4
XS GIS Cut Line= 4
2166607.66127242723039.6737446962166653.87039902722885.138304909
2166675.08114566722791.9625250372166653.87039902722638.184611915
#Sta/Elev= 30
       0 1447.36     2.6 1446.42     6.8 1444.11      11 1443.36    23.5 1442.98
    61.1 1440.67    69.4  1439.2    77.8 1438.53   102.8 1434.75   144.6  1429.8
   177.7  1422.9     206 1422.42   210.5 1422.27   214.6 1421.77   218.7 1420.92
   222.8 1420.72   226.9 1420.98     230 1421.81     231  1422.1   236.7 1425.27
   243.3  1427.7   247.4  1428.9   259.7 1431.04   287.9 1432.36     296 1433.18
   328.3  1437.4   336.7 1438.23   372.7 1443.43   392.9 1446.99   412.1 1449.23
#Mann= 4 ,-1,0
       0     .06       0   214.6    .045       0     230     .06       0
   241.3     .05       0
Bank Sta=214.6,230
XS Rating Curve= 0 ,0
Exp/Cntr(USF)=0,0
Exp/Cntr=0.3,0.1

Type RM Length L Ch R = 1 ,8517    ,154.2,156.4,157.5
XS GIS Cut Line= 3
2166819.76873879722973.7689247872166747.04617889722762.418985078
2166737.95585891722634.396978587
#Sta/Elev= 30
       0 1445.06     9.1 1445.57    17.5 1444.95    30.2 1443.24    42.9  1440.7
    47.2 1439.29    51.4 1437.38    59.8 1432.57      81 1420.98    84.51419.628
    89.5  1418.5    91.4 1418.49    97.9 1418.83   100.9 1419.63   106.4 1421.12
   119.1 1421.33   140.2 1421.08   178.3 1421.56   182.7 1421.76   203.7 1423.77
   220.6  1424.7   224.8 1425.43   232.8 1427.93   240.8 1429.76   256.8 1432.55
     276 1436.39   292.9 1439.18   308.1 1442.48   329.7 1446.63   351.9 1451.14
#Mann= 5 ,-1,0
       0     .06       0    84.5    .045       0   100.9      .1       0
     160     .05       0  293.51      .1       0
Bank Sta=84.5,100.9
XS Rating Curve= 0 ,0
Exp/Cntr(USF)=0,0
Exp/Cntr=0.3,0.1

Type RM Length L Ch R = 1 ,8361    ,183.4,182.3,177.6
XS GIS Cut Line= 2
2166961.84952345 722943.740379312166890.40858995722641.339715617
#Sta/Elev= 30
       0 1447.86     3.5 1447.78    10.9 1448.61    13.5 1448.42    23.2 1446.76
    27.3 1445.26    31.4 1442.85    35.5 1439.92    43.7 1431.62      60 1421.27
    68.4  1419.7   74.381417.718    76.6 1417.16    80.7 1417.01    86.6 1417.72
    88.9 1418.31    97.2 1418.28   105.4  1419.2   117.7  1419.8   154.7 1423.41
   187.6 1425.22   220.5 1424.66     241 1424.71   246.2 1425.09   249.2 1425.53
   256.2 1427.89   265.7 1432.06   275.6    1437   289.4 1442.63   310.7 1449.37
#Mann= 5 ,-1,0
       0     .06       0      60      .1       0   74.38    .045       0
    86.6      .1       0     260     .05       0
Bank Sta=74.38,86.6
XS Rating Curve= 0 ,0
Exp/Cntr(USF)=0,0
Exp/Cntr=0.3,0.1

Type RM Length L Ch R = 1 ,8179    ,102.6,102.3,101.8
XS GIS Cut Line= 2
2167128.83961837722891.1985182342166995.51492522722611.671178618
#Sta/Elev= 30
       0 1442.81    15.5 1439.48      23 1437.29      41 1430.35      47 1427.73
      51 1426.23      59 1423.66    73.1 1421.09      82 1420.26      86 1419.08
    90.9 1416.86      92 1416.58    95.3 1416.23    99.7  1416.5     1031416.937
   108.6  1417.8     113 1418.25   121.9 1418.51   126.3 1419.17     131  1420.1
     140 1420.15   179.5 1423.86   206.1 1423.84   228.3 1423.56   232.7 1423.76
   242.1 1424.81   250.4 1426.69   275.1 1433.54   299.4 1441.94   309.7 1444.72
#Mann= 3 ,-1,0
       0      .1       0    90.9    .045       0     103      .1       0
Bank Sta=90.9,103
XS Rating Curve= 0 ,0
Exp/Cntr(USF)=0,0
Exp/Cntr=0.3,0.1

Type RM Length L Ch R = 1 ,8076    ,53.5,57.5,61.9
XS GIS Cut Line= 3
2167198.53207161722891.9560448992167188.68422495722793.477578368
2167067.47995845722549.553992037
#Sta/Elev= 30
       0    1442    10.8 1441.97    14.9  1441.4    30.9 1436.89    48.5 1433.38
    67.1 1430.35    79.2    1427    95.2 1423.41   120.5 1420.13     144 1417.96
   153.3 1416.65   157.4 1416.02   161.8 1415.92   167.81416.813   175.2 1418.33
   183.1 1421.47   186.1 1422.34   188.6 1422.87   193.1 1423.17   228.8 1423.32
   242.2 1422.89   251.2 1423.22   260.7 1422.51   278.6 1422.82   287.6  1423.3
   299.5 1424.91   313.7  1427.3     336  1432.3   359.2 1436.45   371.3 1439.15
#Mann= 5 ,-1,0
       0     .06       0   98.97      .1       0   153.3    .045       0
   167.8      .1       0  208.97     .05       0
Bank Sta=153.3,167.8
XS Rating Curve= 0 ,0
Exp/Cntr(USF)=0,0
Exp/Cntr=0.3,0.1

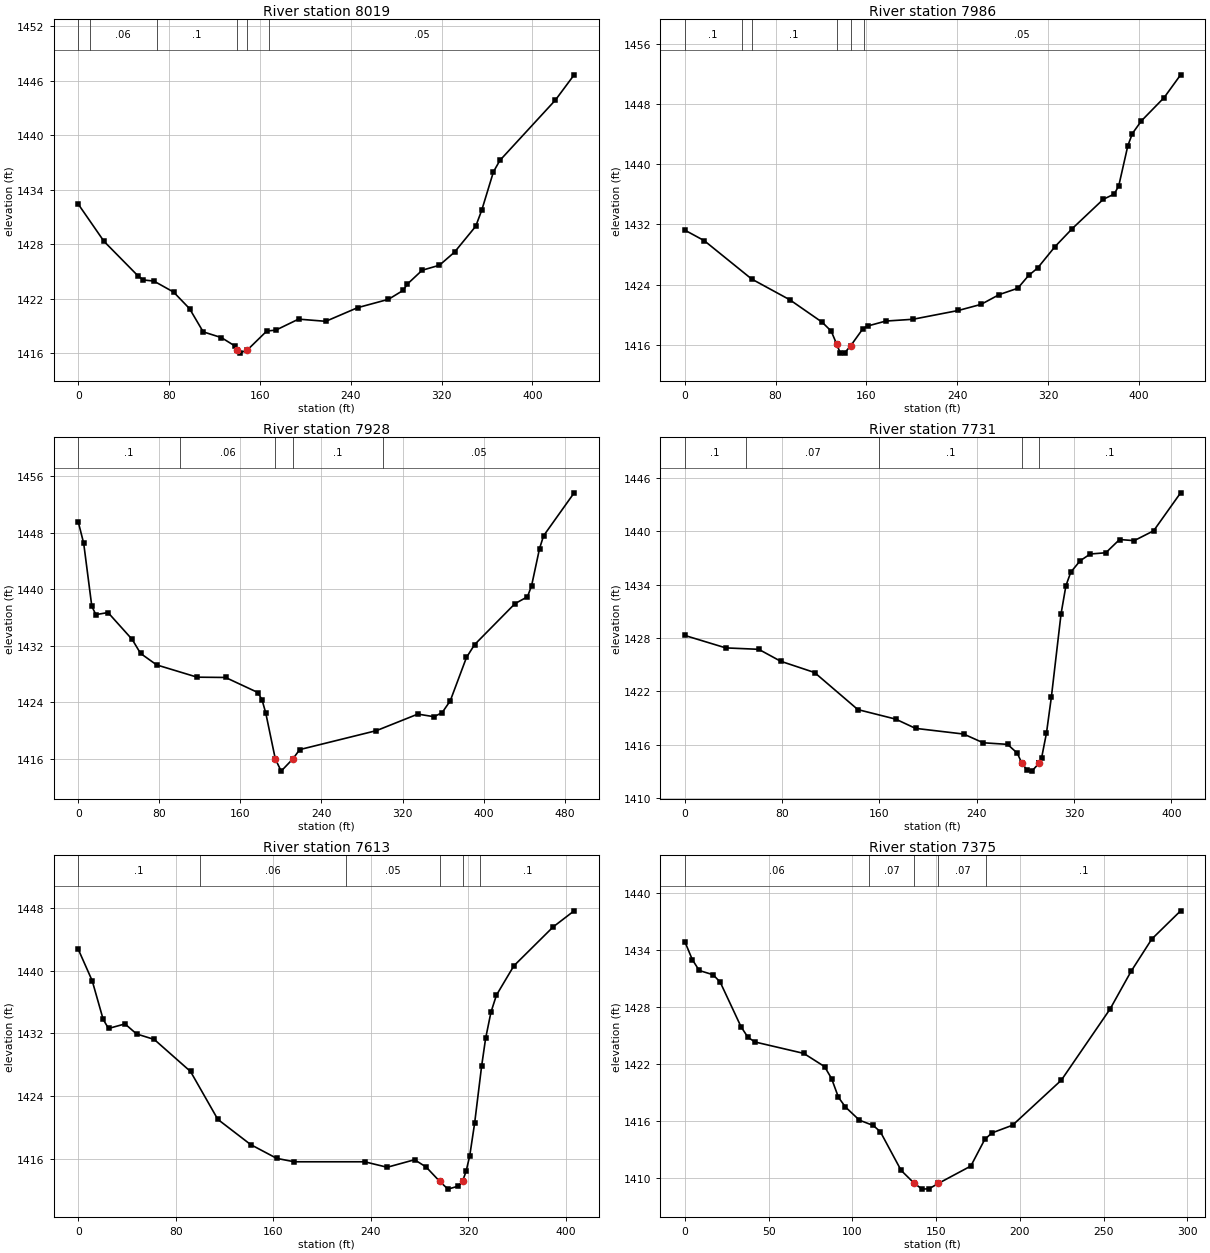
Type RM Length L Ch R = 1 ,8019    ,32.5,33,33.1
XS GIS Cut Line= 6
2167267.84576151722838.9291783062167226.93932157722796.507685031
2167210.27373492722761.6614584122167208.00115493722556.371732027
2167215.57642158722534.4034587242167212.54631492722423.804565543
#Sta/Elev= 30
       0 1432.41    22.6 1428.33    52.4 1424.55    57.2 1424.08    66.5 1423.96
    83.9 1422.75      98 1420.92     110 1418.37     126 1417.74     138 1416.81
     140 1416.42     142 1416.03   148.91416.375     166 1418.46     174 1418.56
     194 1419.77     218 1419.53     246 1421.03   273.2 1421.95   286.1 1422.93
   289.8 1423.62   302.9 1425.15   318.1  1425.7   331.4 1427.14   350.1 1429.99
   355.4 1431.76   365.7 1435.98   371.4 1437.24   420.2 1443.86   436.8 1446.65
#Mann= 6 ,-1,0
       0      .1       0      10     .06       0   68.93      .1       0
     140    .045       0   148.9      .1       0  167.56     .05       0
Bank Sta=140,148.9
XS Rating Curve= 0 ,0
Exp/Cntr(USF)=0,0
Exp/Cntr=0.3,0.1

Type RM Length L Ch R = 1 ,7986    ,62.5,58.3,53.6
XS GIS Cut Line= 6
 2167300.0406448722829.8388583182167259.13420486722787.417365043
2167242.46861821722752.5711384242167240.19603822 722547.28141204
2167247.77130487722525.3131387372167244.74119821722414.714245555
#Sta/Elev= 30
       0 1431.23    17.1 1429.83    58.9 1424.73    92.5 1421.97     121 1418.99
     129  1417.8   133.91416.036     137 1414.88     141 1414.95     1461415.834
     157 1418.14     161 1418.48     177 1419.14     201 1419.38     241 1420.55
     261 1421.36     277 1422.66   293.3  1423.5   302.9  1425.2   310.8 1426.19
   326.1 1429.03   341.4 1431.44   368.7 1435.33   378.3 1436.02   382.3 1437.12
   390.3 1442.45   394.3 1444.07   402.3 1445.76   422.3 1448.85   436.8 1451.87
#Mann= 6 ,-1,0
       0      .1       0      50     .06       0   58.93      .1       0
   133.9    .045       0     146      .1       0  157.56     .05       0
Bank Sta=133.9,146
XS Rating Curve= 0 ,0
Exp/Cntr(USF)=0,0
Exp/Cntr=0.3,0.1

Type RM Length L Ch R = 1 ,7928    ,188.8,196.4,202.3
XS GIS Cut Line= 4
2167303.82827813722890.4409915682167305.34333146722710.149645149
2167256.86162486 722595.763118642167261.40678485722410.926612227
#Sta/Elev= 30
       0 1449.52     5.3 1446.52    13.3 1437.61    17.3 1436.42    29.3 1436.72
    53.2  1432.9    61.4 1430.93    77.3  1429.3   117.3 1427.56   145.3 1427.52
   177.3 1425.38   181.4 1424.31     185 1422.48   194.4 1415.99   200.2 1414.25
   211.8 1415.99   218.5  1417.3   294.3 1419.99   335.1 1422.33   351.1 1421.96
   359.1 1422.54   367.1 1424.21   383.1 1430.35   391.1 1432.17     431 1437.98
   443.3 1438.95   447.4 1440.53   455.2 1445.77   459.2 1447.59   489.4 1453.68
#Mann= 5 ,-1,0
       0      .1       0     100     .06       0   194.4    .045       0
   211.8      .1       0   300.3     .05       0
Bank Sta=194.4,211.8
XS Rating Curve= 0 ,0
Exp/Cntr(USF)=0,0
Exp/Cntr=0.3,0.1

Type RM Length L Ch R = 1 ,7731    ,112.1,118.2,123.6
XS GIS Cut Line= 3
2167346.36482301722831.1421508922167442.08589248722646.449574545
2167451.90343807722447.030679818
#Sta/Elev= 30
       0 1428.29    33.7 1426.89    60.8 1426.73    78.8 1425.39   106.7 1424.12
   142.3 1419.95   173.4 1418.88   189.7 1417.84   229.3  1417.2   245.3 1416.22
   265.4 1416.04   273.4 1415.05   277.21413.907   281.4 1413.16   285.4 1413.03
   291.4 1413.94   291.4 1413.95   293.4 1414.53   297.4 1417.32   301.4 1421.34
   309.4 1430.74   313.4 1433.89   317.4 1435.41   325.1 1436.69   333.4 1437.45
   346.2 1437.59   357.5 1439.08   369.5 1438.95   385.5 1440.06   407.7 1444.33
#Mann= 5 ,-1,0
       0      .1       0      50     .07       0     160      .1       0
   277.2    .045       0   291.4      .1       0
Bank Sta=277.2,291.4
XS Rating Curve= 0 ,0
Exp/Cntr(USF)=0,0
Exp/Cntr=0.3,0.1

Type RM Length L Ch R = 1 ,7613    ,240.5,238.4,235.7
XS GIS Cut Line= 2
2167414.55792683722887.3418185162167598.54279665722524.265293499
#Sta/Elev= 30
       0 1442.72    11.4 1438.72    20.4 1433.79    24.8 1432.64    38.3 1433.22
    47.8 1431.94    62.3 1431.24    92.1 1427.15   114.5 1421.04   141.4 1417.83
   162.9 1416.06   177.3 1415.63     235 1415.63   253.5 1414.93     276 1415.89
   285.5 1414.96  296.69 1413.12   303.4 1412.14   311.8 1412.52  315.361413.137
   318.3 1414.42   321.3 1416.41   325.3 1420.55     331 1427.79   334.3 1431.36
   338.7 1434.71   343.2 1436.89   357.5 1440.63   389.7 1445.59     407 1447.65
#Mann= 6 ,-1,0
       0      .1       0     100     .06       0     220     .05       0
  296.69    .045       0  315.36     .05       0     330      .1       0
Bank Sta=296.69,315.36
XS Rating Curve= 0 ,0
Exp/Cntr(USF)=0,0
Exp/Cntr=0.3,0.1

Type RM Length L Ch R = 1 ,7375    ,93.7,92.2,90.7
XS GIS Cut Line= 2
2167705.31741091722893.4710982312167785.61523747722608.641071956
#Sta/Elev= 30
       0 1434.85     4.5 1432.95     8.6 1431.81    16.9 1431.36    21.1 1430.59
    33.6 1425.87    37.7 1424.77    41.9 1424.28      71 1423.08    83.4 1421.69
    87.6 1420.43    91.7 1418.45    95.9 1417.43   104.2 1416.05   112.5 1415.49
   116.7 1414.83   129.1 1410.76   136.91409.409   141.6 1408.79   145.8 1408.83
  151.39  1409.4   170.7 1411.22     179 1414.02   183.2  1414.7   195.6 1415.52
   224.7 1420.26   253.8 1427.75   266.3 1431.71   278.7 1435.12   295.9 1438.09
#Mann= 5 ,-1,0
       0     .06       0     110     .07       0   136.9    .045       0
  151.39     .07       0     180      .1       0
Bank Sta=136.9,151.39
XS Rating Curve= 0 ,0
Exp/Cntr(USF)=0,0
Exp/Cntr=0.3,0.1

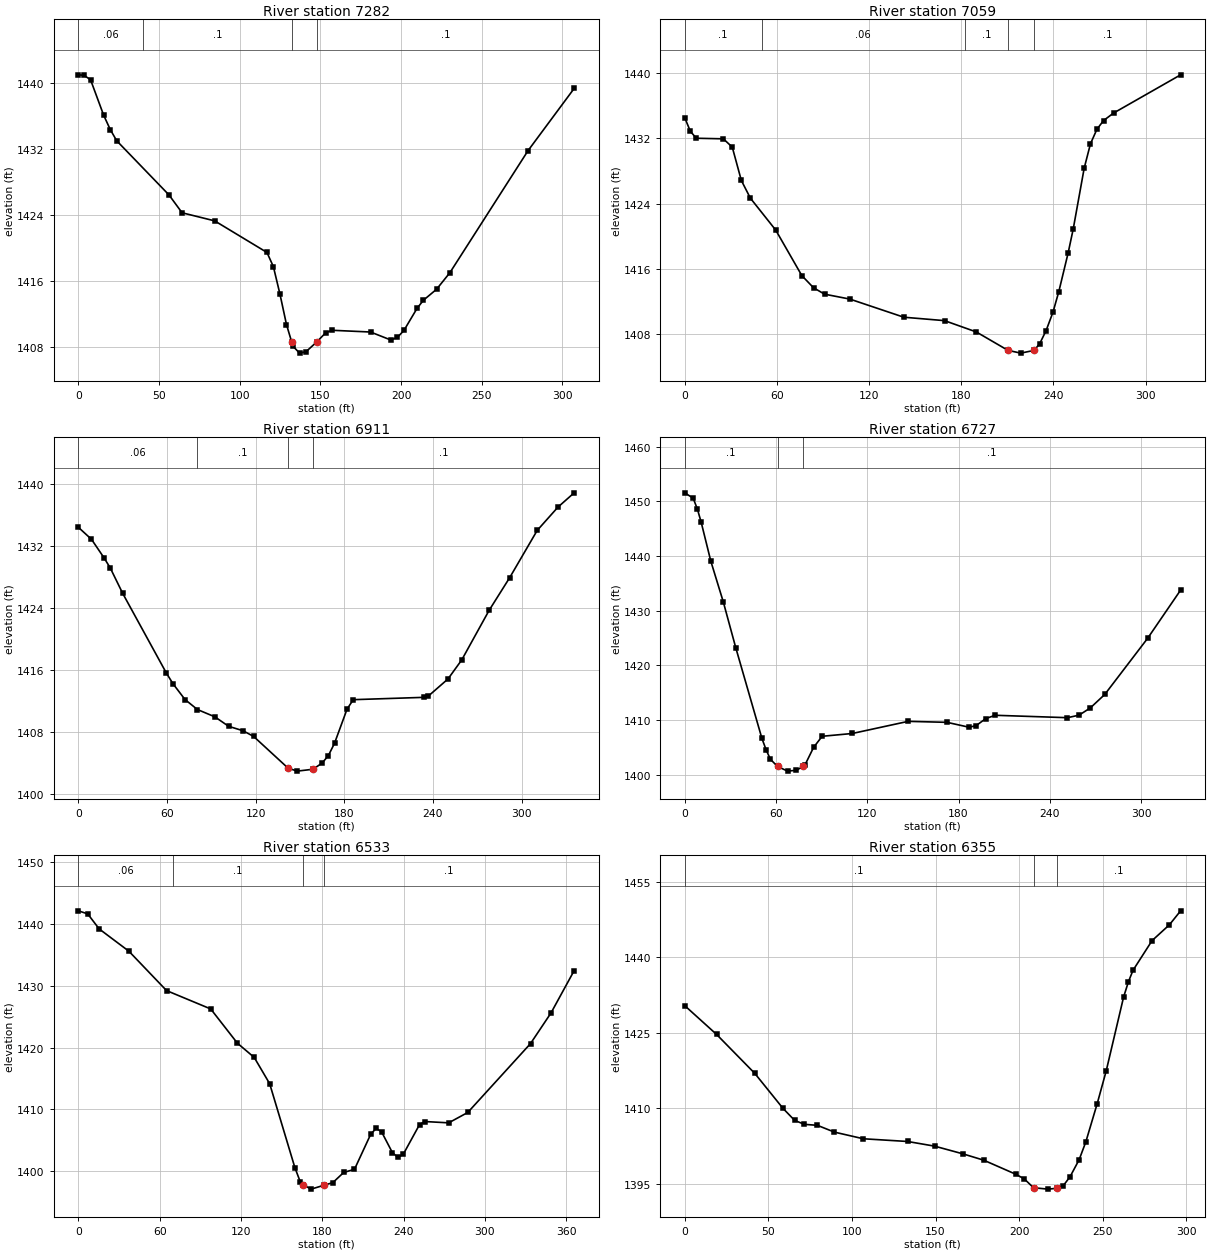
Type RM Length L Ch R = 1 ,7282    ,221.3,223.5,223.3
XS GIS Cut Line= 2
 2167809.7021089722924.7364343962167855.50259777722620.867806315
#Sta/Elev= 30
       0 1441.03     3.6 1440.97     7.6 1440.42    15.7 1436.13    19.8 1434.39
    23.8 1433.03    56.2 1426.46    64.3  1424.3    84.5 1423.32   116.9 1419.49
   120.9 1417.76     125  1414.4     129 1410.75  132.211408.647     133 1408.13
   137.1 1407.28   141.1 1407.45  147.911408.665   153.3 1409.75   157.3 1410.05
   181.1 1409.84   193.7 1408.87   197.8  1409.2   201.8 1410.03   209.9  1412.7
   213.9  1413.7     222 1415.02   230.3 1417.04   278.7 1431.83   307.3 1439.38
#Mann= 4 ,-1,0
       0     .06       0      40      .1       0  132.21    .045       0
  147.91      .1       0
Bank Sta=132.21,147.91
XS Rating Curve= 0 ,0
Exp/Cntr(USF)=0,0
Exp/Cntr=0.3,0.1

Type RM Length L Ch R = 1 ,7059    ,147.3,148.3,149.2
XS GIS Cut Line= 3
2167901.51681731722922.2571115252168020.44850381722811.658218343
2168060.59741709 722656.36525189
#Sta/Elev= 30
       0 1434.54     3.6 1432.89     7.5 1432.03    25.1 1431.96    30.9 1430.94
    36.8 1426.85    42.7 1424.67    59.2 1420.75    76.2 1415.16    83.8 1413.67
      91 1412.88   107.4 1412.28   142.6 1410.05   169.1 1409.63   189.8 1408.24
   210.4 1405.98   218.7 1405.64   227.5 1405.98   231.1 1406.82   235.2  1408.4
   239.7 1410.67   243.5  1413.2   249.6 1417.97   252.9 1420.91     260 1428.34
   264.1 1431.35   268.3 1433.13   272.6  1434.2   279.1 1435.12   322.8 1439.82
#Mann= 5 ,-1,0
       0      .1       0      50     .06       0  182.41      .1       0
   210.4    .045       0   227.5      .1       0
Bank Sta=210.4,227.5
XS Rating Curve= 0 ,0
Exp/Cntr(USF)=0,0
Exp/Cntr=0.3,0.1

Type RM Length L Ch R = 1 ,6911    ,195.2,183.2,165.7
XS GIS Cut Line= 3
2168119.68449701722961.6484981372168181.80168359722776.054465059
2168110.59417702722655.607725224
#Sta/Elev= 30
       0 1434.38     8.9 1432.83    17.4 1430.44    21.6 1429.14      30 1425.87
    59.5 1415.62      64 1414.23    72.2 1412.18    80.6 1410.89    92.4 1409.95
   101.7 1408.73   111.4 1408.16   118.6 1407.43   141.91403.347   148.1 1402.95
   158.8 1403.19     165 1403.99   169.2 1404.94   173.4 1406.54   181.9 1410.95
   186.1 1412.16     234 1412.46     237 1412.64   250.2 1414.83   259.5 1417.28
     278 1423.66     292  1427.9   310.6 1433.98   324.7 1436.99   335.6 1438.82
#Mann= 4 ,-1,0
       0     .06       0      80      .1       0   141.9    .045       0
   158.8      .1       0
Bank Sta=141.9,158.8
XS Rating Curve= 0 ,0
Exp/Cntr(USF)=0,0
Exp/Cntr=0.3,0.1

Type RM Length L Ch R = 1 ,6727    ,202.2,194.1,181
XS GIS Cut Line= 2
2168376.32463157722872.7812545552168144.71247275722643.343857793
#Sta/Elev= 30
       0 1451.54     5.5 1450.56     8.3 1448.55    10.8 1446.13    17.1 1439.05
    25.3 1431.61    33.5 1423.23    50.7 1406.64    53.6 1404.46    56.3 1402.83
   60.951401.512    67.6 1400.66    73.4 1400.82   77.711401.508      79 1401.78
    84.7 1405.01    90.3 1407.03   110.1 1407.54   146.9 1409.76   172.4 1409.58
     187 1408.68   191.6 1408.99   197.8 1410.25     204 1410.87   251.6 1410.43
   259.2 1410.89   266.6 1412.21   276.1 1414.67   304.3 1424.94     326 1433.76
#Mann= 3 ,-1,0
       0      .1       0   60.95    .045       0   77.71      .1       0
Bank Sta=60.95,77.71
XS Rating Curve= 0 ,0
Exp/Cntr(USF)=0,0
Exp/Cntr=0.3,0.1

Type RM Length L Ch R = 1 ,6533    ,168.9,178,186.9
XS GIS Cut Line= 4
2168492.38761649722742.7232917712168404.51452328722639.699665246
2168273.46241013722641.214718577 2168194.6796369722580.612585327
#Sta/Elev= 30
       0 1442.11     6.9 1441.62    15.4 1439.18    37.3 1435.58    65.1 1429.21
    97.7 1426.24   117.4  1420.7   129.8  1418.4   141.2 1414.15   159.8 1400.58
   163.8 1398.27   165.61397.838   171.8  1397.1   181.51397.742   187.8 1398.15
   195.8 1399.79   203.8 1400.31   215.8 1405.99   219.8 1406.93   223.8 1406.36
   231.8 1402.99   235.8 1402.25   239.8 1402.74   251.8 1407.54   255.8 1408.03
   273.3 1407.82   287.4  1409.5   333.7 1420.64   348.8 1425.59   365.9 1432.44
#Mann= 4 ,-1,0
       0     .06       0      70      .1       0   165.6    .045       0
   181.5      .1       0
Bank Sta=165.6,181.5
XS Rating Curve= 0 ,0
Exp/Cntr(USF)=0,0
Exp/Cntr=0.3,0.1

Type RM Length L Ch R = 1 ,6355    ,202.5,206.1,208.8
XS GIS Cut Line= 2
2168518.90104979722625.3066585992168299.21831676 722426.07714554
#Sta/Elev= 30
       0 1430.39      19 1424.69    41.9 1416.94    58.7 1410.02    65.7 1407.62
    71.6 1406.83    79.3 1406.64    89.5 1405.29   106.8 1403.97   133.3 1403.43
   149.5  1402.5   166.3 1400.98   178.8 1399.72   198.1 1396.91   203.1 1395.99
   208.6 1394.25   217.2 1393.97   222.9 1394.14   226.5 1394.69   230.5 1396.46
   235.9 1399.82   239.9 1403.36   246.7 1410.95   252.1 1417.47   262.5 1432.13
   265.4 1435.17   268.1 1437.41   279.5 1443.31   289.9 1446.46   296.6 1449.23
#Mann= 3 ,-1,0
       0      .1       0   208.6    .045       0   222.9      .1       0
Bank Sta=208.6,222.9
XS Rating Curve= 0 ,0
Exp/Cntr(USF)=0,0
Exp/Cntr=0.3,0.1