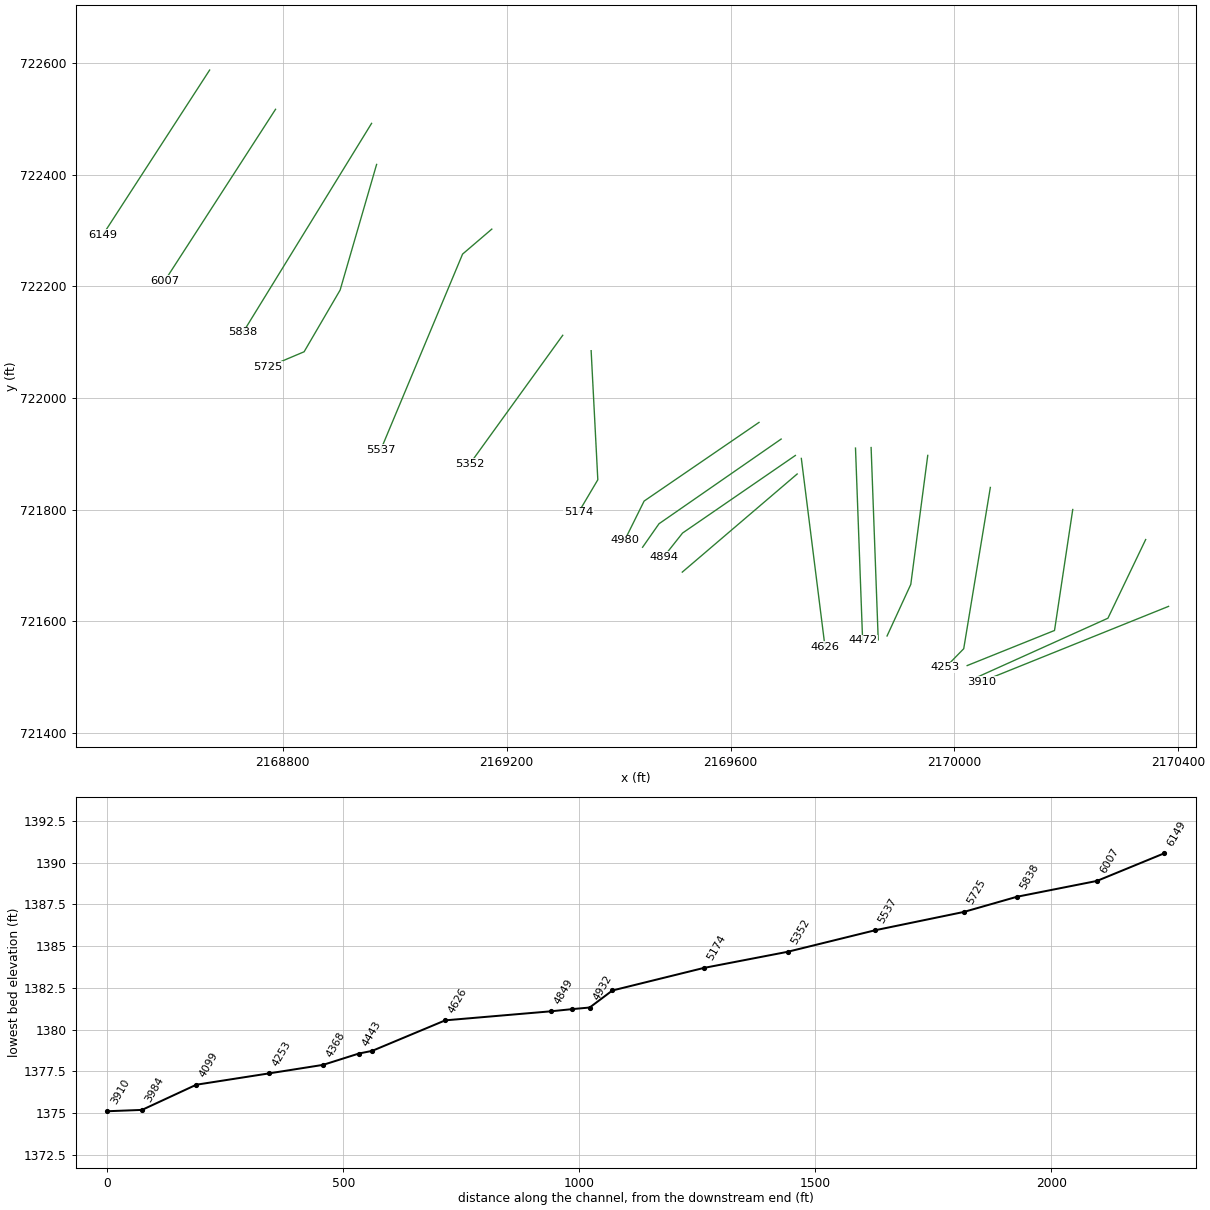
HEC-RAS study SPRUCEFK.prj: SPRUCEFK

--- SPRUCEFK.g01 (geometry) --- (continued)

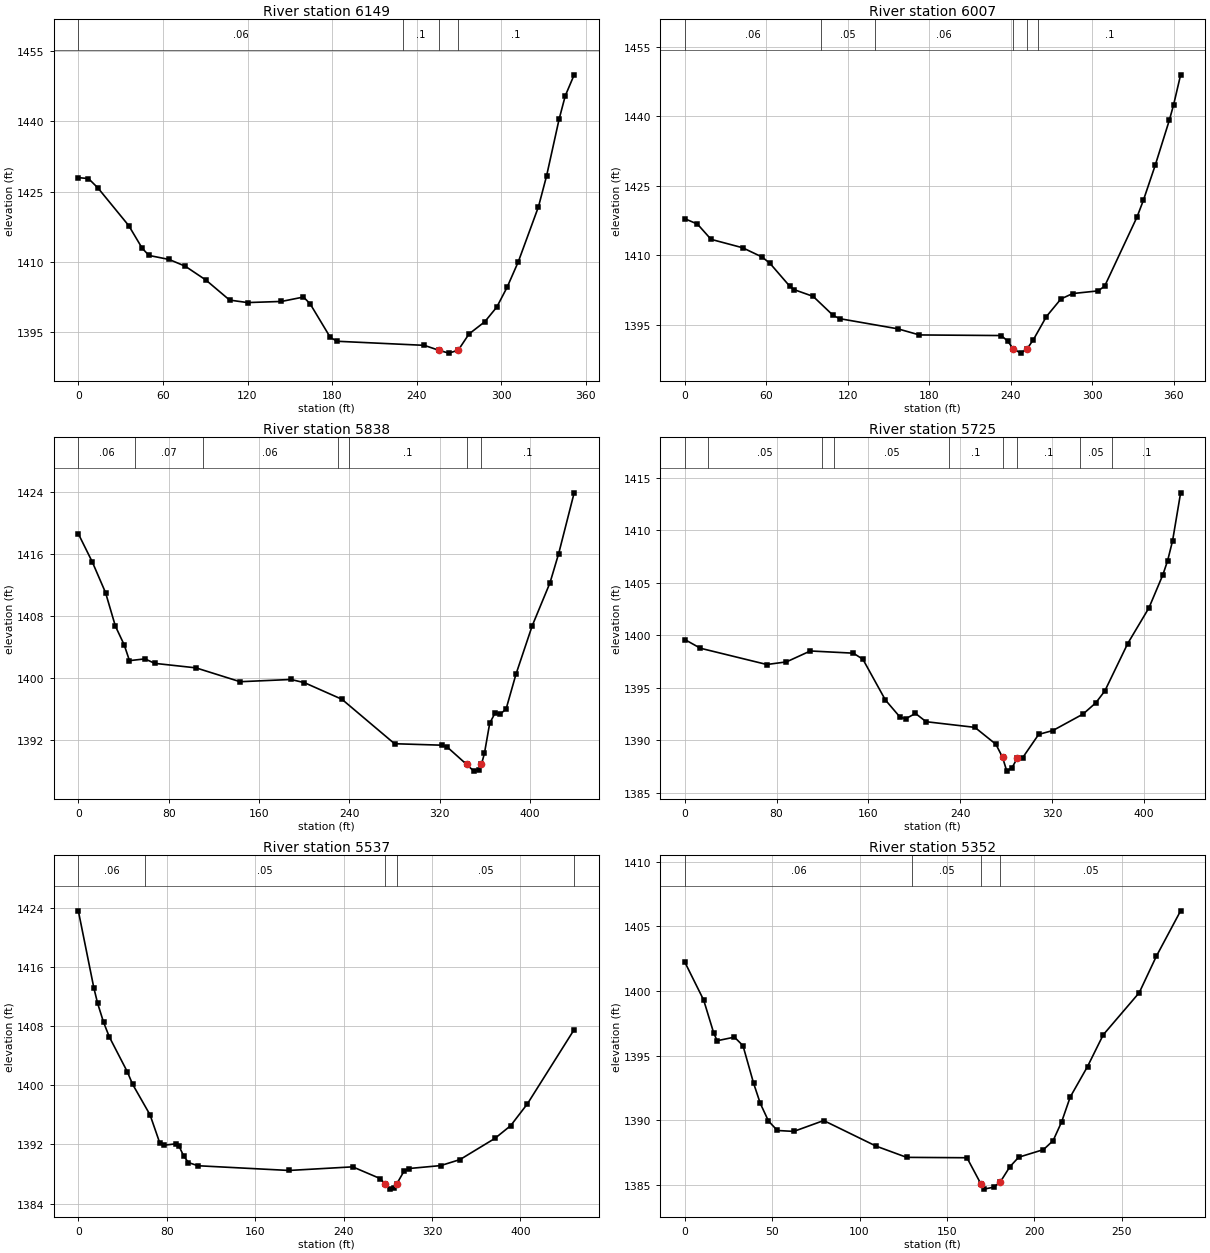
Type RM Length L Ch R = 1 ,6149    ,141.6,142,141.8
XS GIS Cut Line= 2
2168669.30045656722587.2603203092168478.37484409 722291.92226351
#Sta/Elev= 30
       0 1427.98     7.2 1427.78    13.9 1425.78    35.8 1417.73    45.3 1412.92
    50.1 1411.39    64.4 1410.53    75.8  1409.1    90.5 1406.14   107.3 1401.87
     120 1401.34   144.1 1401.58   159.7 1402.52   164.4 1401.08   178.7 1393.93
   183.5 1393.09   245.4 1392.22  255.681391.173   262.7 1390.56  269.431391.167
   277.1 1394.64   288.3 1397.25   296.8 1400.37   304.2 1404.64   312.1 1410.06
   326.4 1421.79   332.1  1428.3     341 1440.41   345.4 1445.43   351.7  1449.9
#Mann= 4 ,-1,0
       0     .06       0     230      .1       0  255.68    .045       0
  269.43      .1       0
Bank Sta=255.68,269.43
XS Rating Curve= 0 ,0
Exp/Cntr(USF)=0,0
Exp/Cntr=0.3,0.1

Type RM Length L Ch R = 1 ,6007    ,169.1,169.6,169.5
XS GIS Cut Line= 2
2168787.06548942722516.9803454152168589.35102969722210.182045837
#Sta/Elev= 30
       0 1417.88     9.3 1416.73    19.3 1413.44    42.5 1411.63    56.9 1409.63
    62.7 1408.26    77.2 1403.35    80.7 1402.57    94.5 1401.14   109.2 1397.04
     114 1396.34   156.8 1394.15   172.7 1392.83   232.9  1392.7   237.7 1391.51
   241.6  1389.9   247.2 1388.91     252 1389.85   256.6  1391.8   266.2  1396.8
   276.9 1400.59   285.5 1401.75   304.3 1402.33   309.1 1403.36   332.9 1418.25
   337.6 1421.87   346.3 1429.41   356.7 1439.13   359.8 1442.41     365  1448.9
#Mann= 6 ,-1,0
       0     .06       0     100     .05       0     140     .06       0
   241.6    .045       0     252     .06       0     260      .1       0
Bank Sta=241.6,252
XS Rating Curve= 0 ,0
Exp/Cntr(USF)=0,0
Exp/Cntr=0.3,0.1

Type RM Length L Ch R = 1 ,5838    ,111.9,112.5,112.7
XS GIS Cut Line= 2
2168958.67208797722491.7975140712168728.96471046722117.404320856
#Sta/Elev= 30
       0 1418.62    12.4 1414.97    24.1 1411.02    32.8  1406.7    40.6 1404.28
    45.3 1402.23      59 1402.46    67.7 1401.88   104.2  1401.3   143.3 1399.51
   188.3  1399.8   200.2 1399.39   233.5 1397.24   280.1  1391.5   322.2 1391.31
   326.9 1391.05     344 1388.82   350.3 1387.96     355 1388.11  357.051388.828
   359.7 1390.24   364.4 1394.15   369.1 1395.45   373.8 1395.34   378.9 1395.98
   387.6 1400.45     402 1406.72   417.8 1412.29   425.5 1416.07   439.2 1423.91
#Mann= 7 ,-1,0
       0     .06       0      50     .07       0     110     .06       0
     230     .05       0     240      .1       0     344    .045       0
  357.05      .1       0
Bank Sta=344,357.05
XS Rating Curve= 0 ,0
Exp/Cntr(USF)=0,0
Exp/Cntr=0.3,0.1

Type RM Length L Ch R = 1 ,5725    ,186.1,188.3,189
XS GIS Cut Line= 4
  2168967.639595 722418.235745832168902.49230175722193.250326139
2168838.10253517722082.651432958 2168773.7127686722055.380472995
#Sta/Elev= 30
       0 1399.59    13.6 1398.76    71.5 1397.21    88.6 1397.46   109.4  1398.5
   146.9 1398.29   155.2 1397.71   174.8 1393.83   187.7 1392.18   192.7 1392.05
     201 1392.55   210.3 1391.76   252.8 1391.22   271.1 1389.61   276.9 1388.37
   280.6 1387.05   285.2 1387.38   289.9 1388.32   294.5 1388.34   308.4 1390.55
   320.8 1390.92   347.1 1392.49   358.1 1393.55     366 1394.68     386 1399.21
   404.5 1402.61   416.7 1405.78   420.8 1407.12   425.1 1409.01   432.1 1413.57
#Mann= 9 ,-1,0
       0     .06       0      20     .05       0     120     .06       0
     130     .05       0     230      .1       0   276.9    .045       0
   289.9      .1       0  344.23     .05       0   372.2      .1       0
Bank Sta=276.9,289.9
XS Rating Curve= 0 ,0
Exp/Cntr(USF)=0,0
Exp/Cntr=0.3,0.1

Type RM Length L Ch R = 1 ,5537    ,187.3,185.1,182.6
XS GIS Cut Line= 3
2169173.46340201722302.3635079422169121.25717985722257.615317518
2168975.07975779721907.087825862
#Sta/Elev= 30
       0 1423.67    14.1 1413.18    17.5 1411.11    22.8 1408.58      28 1406.59
    44.3 1401.86    49.1 1400.16    64.9 1396.01    73.6 1392.24    77.9 1391.91
    88.3 1392.09    90.9 1391.84    95.2 1390.47    99.6 1389.55   108.2 1389.12
   190.6 1388.48   248.2 1388.97   272.9 1387.39   277.3  1386.7   281.6 1385.95
   285.9 1386.08  288.181386.694   294.6 1388.37   298.9 1388.74   327.8 1389.14
   345.2 1389.95   376.9 1392.83   391.1 1394.55   406.3 1397.52   448.5 1407.56
#Mann= 5 ,-1,0
       0     .06       0      60     .05       0   277.3    .045       0
  288.18     .05       0  448.55      .1       0
Bank Sta=277.3,288.18
XS Rating Curve= 0 ,0
Exp/Cntr(USF)=0,0
Exp/Cntr=0.3,0.1

Type RM Length L Ch R = 1 ,5352    ,170.2,178,184.3
XS GIS Cut Line= 2
 2169300.1938012722112.1949729172169134.29546143721881.906866567
#Sta/Elev= 30
       0 1402.24    10.8  1399.3    16.5 1396.77    18.5 1396.15    28.4 1396.43
    33.3 1395.77    39.4 1392.85    43.2  1391.3    47.9 1389.93      53  1389.2
    62.4 1389.13    79.5 1389.97   109.5 1387.99     127 1387.12   161.5 1387.09
   169.51385.059   171.3 1384.66     177 1384.82   180.6 1385.22   186.1  1386.4
   191.1 1387.13   205.3 1387.72   210.8 1388.41   215.7 1389.87   220.6 1391.79
   230.5 1394.15   239.5 1396.61   260.1 1399.87   269.9 1402.69   283.8 1406.21
#Mann= 4 ,-1,0
       0     .06       0     130     .05       0   169.5    .045       0
   180.6     .05       0
Bank Sta=169.5,180.6
XS Rating Curve= 0 ,0
Exp/Cntr(USF)=0,0
Exp/Cntr=0.3,0.1

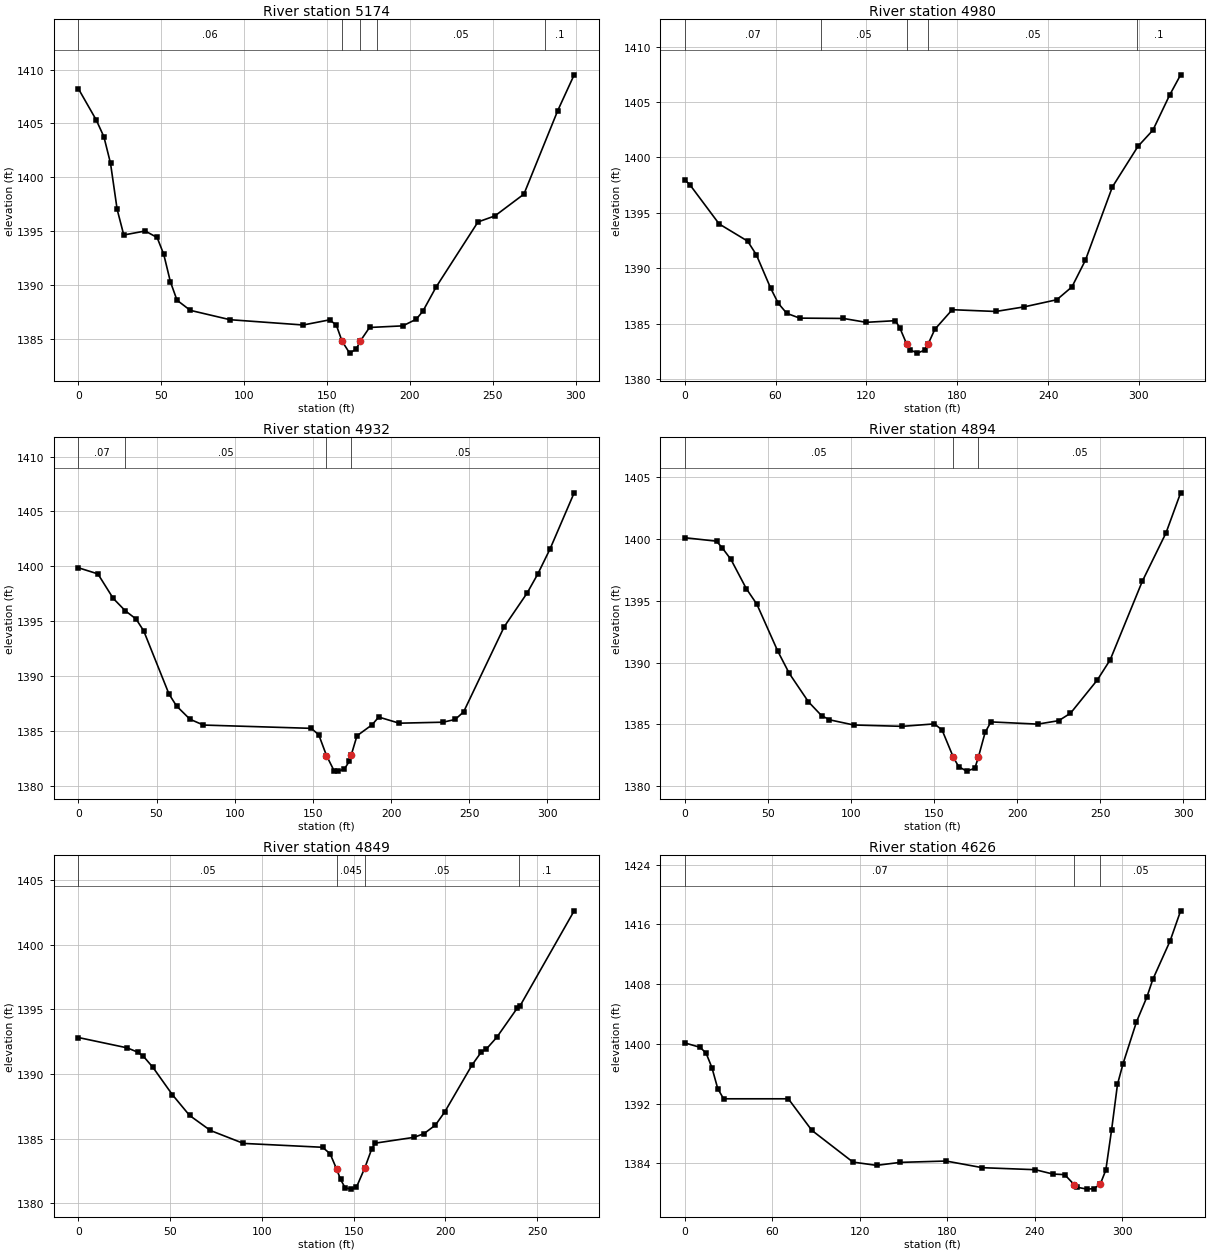
Type RM Length L Ch R = 1 ,5174    ,205.2,193.4,181.3
XS GIS Cut Line= 3
2169350.96455736722084.5889812112169362.89740814721853.389997353
2169328.59046215721795.217349802
#Sta/Elev= 30
       0 1408.23    10.8 1405.32    15.4 1403.77    19.4 1401.31    23.4 1397.03
    27.4 1394.65    40.3 1395.02    47.5 1394.42    51.5 1392.86    55.5 1390.32
    59.5  1388.6    67.5 1387.66    91.5 1386.79   135.6  1386.3   151.6 1386.78
   155.6 1386.28  159.041384.796   163.6 1383.69   167.6 1384.07  169.961384.794
   175.6 1386.07   195.7 1386.22   203.7 1386.83   207.7 1387.56   215.7 1389.81
     241 1395.86   251.2 1396.42   268.7 1398.44   289.1 1406.19     299 1409.51
#Mann= 5 ,-1,0
       0     .06       0  159.04    .045       0  169.96     .06       0
     180     .05       0  281.51      .1       0
Bank Sta=159.04,169.96
XS Rating Curve= 0 ,0
Exp/Cntr(USF)=0,0
Exp/Cntr=0.3,0.1

Type RM Length L Ch R = 1 ,4980    ,47.9,48,48.1
XS GIS Cut Line= 3
2169650.92864739721956.144479799  2169445.638921721815.244519992
2169410.79269439721744.794540089
#Sta/Elev= 30
       0 1397.98     3.3 1397.55    22.7    1394    41.5 1392.45    47.3 1391.21
    56.7 1388.21    61.8 1386.83    67.4 1385.93    75.9  1385.5   104.8 1385.47
   119.8 1385.12   139.2 1385.27   142.2 1384.58   146.6 1383.16   148.9 1382.63
   153.7 1382.34   158.6 1382.62   160.7 1383.14   165.2 1384.49   176.7 1386.26
   205.5  1386.1   224.4 1386.52   245.8 1387.16   255.8 1388.32   264.7 1390.73
   282.5 1397.34   299.4    1401   309.3 1402.47   320.3 1405.62   327.6 1407.46
#Mann= 5 ,-1,0
       0     .07       0      90     .05       0   146.6    .045       0
   160.7     .05       0  298.99      .1       0
Bank Sta=146.6,160.7
XS Rating Curve= 0 ,0
Exp/Cntr(USF)=0,0
Exp/Cntr=0.3,0.1

Type RM Length L Ch R = 1 ,4932    ,38,38.1,38
XS GIS Cut Line= 3
 2169690.4690781721926.3010580632169472.23170592721774.611404754
2169442.87241819721732.529758997
#Sta/Elev= 30
       0 1399.86    12.5  1399.3    22.3 1397.07      30 1395.94    36.9 1395.19
    41.8 1394.11      58 1388.34    62.8 1387.26    71.4 1386.05      80 1385.52
     149 1385.22   153.8 1384.62   158.7 1382.74   163.5 1381.37   166.3 1381.32
   170.2 1381.52   173.3 1382.22  174.451382.745   178.2 1384.54   187.9 1385.55
   192.1 1386.25   205.2 1385.69   233.2 1385.78     241 1386.03   246.4 1386.72
   272.4 1394.49     287 1397.55   293.8 1399.28   301.7 1401.58   317.1 1406.69
#Mann= 4 ,-1,0
       0     .07       0      30     .05       0   158.7    .045       0
  174.45     .05       0
Bank Sta=158.7,174.45
XS Rating Curve= 0 ,0
Exp/Cntr(USF)=0,0
Exp/Cntr=0.3,0.1

Type RM Length L Ch R = 1 ,4894    ,43.7,44.9,46.3
XS GIS Cut Line= 3
2169715.91379414721896.9417703262169514.31335168721757.974475036
2169481.03949225 721715.89282928
#Sta/Elev= 30
       0 1400.09    19.1 1399.81    22.6 1399.26    27.8 1398.33      37 1395.98
    43.4 1394.71      56 1390.91    62.9 1389.12    74.4 1386.83    82.3 1385.71
    87.1 1385.37   101.7 1384.95   130.9 1384.84   150.3 1385.04   154.9 1384.54
   161.7 1382.33   164.9 1381.58   169.7 1381.22   174.6 1381.45  176.711382.328
   180.8 1384.35   184.3  1385.2   212.5 1385.02   225.1  1385.3   232.2  1385.9
   248.3 1388.58   256.1 1390.22   275.4 1396.56   289.7 1400.48   298.5 1403.72
#Mann= 3 ,-1,0
       0     .05       0   161.7    .045       0  176.71     .05       0
Bank Sta=161.7,176.71
XS Rating Curve= 0 ,0
Exp/Cntr(USF)=0,0
Exp/Cntr=0.3,0.1

Type RM Length L Ch R = 1 ,4849    ,211.5,223.1,238.5
XS GIS Cut Line= 2
 2169719.1060473721863.7262265922169513.81632091721687.980040167
#Sta/Elev= 30
       0 1392.83    26.6 1392.03    32.3  1391.7    35.5 1391.37    40.7 1390.51
    51.2 1388.41    60.6  1386.8      72 1385.63      90 1384.63   133.1 1384.33
   137.2 1383.83   140.8 1382.63   142.9 1381.84   145.4 1381.19   148.6 1381.09
   151.5 1381.22   156.1 1382.73   159.9 1384.21   161.8 1384.65   182.9  1385.1
   188.3 1385.38   194.6 1386.05   199.6 1387.05   214.5 1390.69   219.7 1391.73
   222.3 1391.93     228 1392.84   239.3 1395.13   240.8  1395.3   270.2 1402.64
#Mann= 4 ,-1,0
       0     .05       0   140.8    .045       0   156.1     .05       0
     240      .1       0
Bank Sta=140.8,156.1
XS Rating Curve= 0 ,0
Exp/Cntr(USF)=0,0
Exp/Cntr=0.3,0.1

Type RM Length L Ch R = 1 ,4626    ,152.3,154.8,159.2
XS GIS Cut Line= 2
2169726.54744088721891.6164224282169768.82481522721554.278206327
#Sta/Elev= 30
       0 1400.12    10.5 1399.53    14.6 1398.75    18.6 1396.81    22.6    1394
    26.6 1392.64      71 1392.64    87.1 1388.42   115.3 1384.17   131.5 1383.73
   147.6 1384.13   179.2 1384.31     204 1383.42   240.3 1383.15   252.4 1382.57
   260.5 1382.49  267.151381.121   268.7 1380.81   275.9 1380.55   280.6 1380.62
  284.931381.228   288.7  1383.1   292.7 1388.53   296.7 1394.57   300.5 1397.33
   309.7 1402.92   316.9 1406.28   320.9 1408.61   332.8 1413.78     340  1417.8
#Mann= 3 ,-1,0
       0     .07       0  267.15    .045       0  284.93     .05       0
Bank Sta=267.15,284.93
XS Rating Curve= 0 ,0
Exp/Cntr(USF)=0,0
Exp/Cntr=0.3,0.1

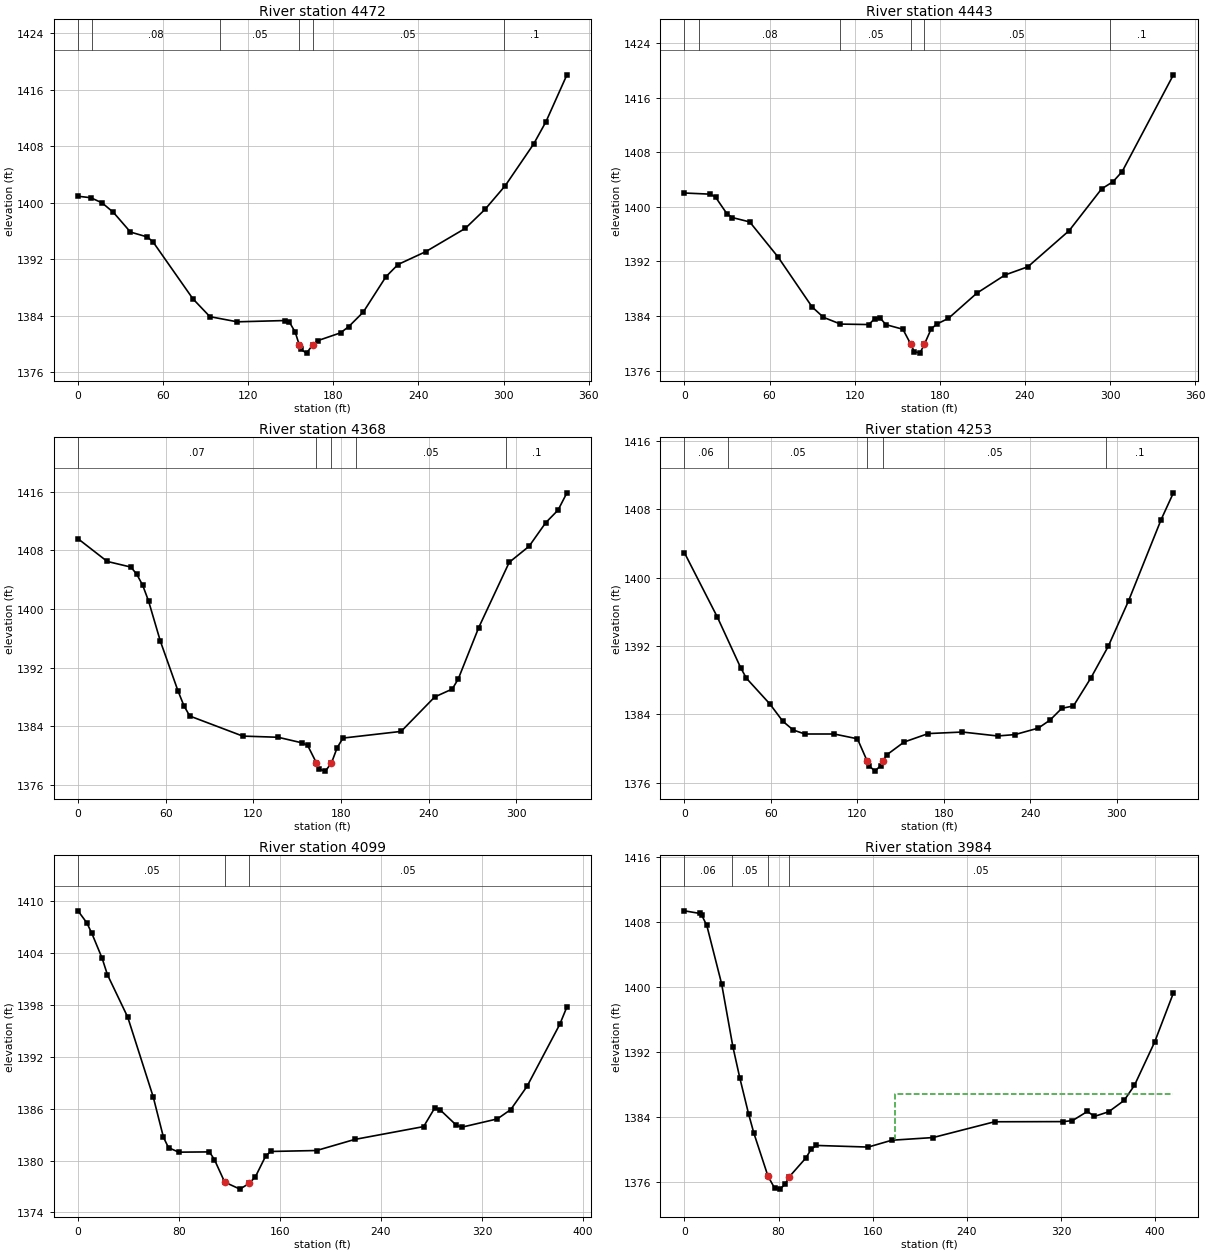
Type RM Length L Ch R = 1 ,4472    ,28.1,28.2,28.3
XS GIS Cut Line= 2
2169823.32542627721910.1298227632169836.04778429721565.647513313
#Sta/Elev= 30
       0 1400.92       9 1400.71      17 1399.98      25 1398.63      37 1395.85
      49 1395.15      53 1394.43      81 1386.41      93 1383.88   112.3 1383.15
   145.6 1383.33   149.1 1383.08   153.1 1381.71   156.1 1379.82   157.1 1379.25
   161.1 1378.72  165.341379.843   169.1 1380.49   185.1 1381.59   190.9 1382.48
   201.1 1384.52   217.1 1389.53   225.6 1391.26   245.1 1393.07   273.1 1396.38
   286.9 1399.05   301.2 1402.41   321.2  1408.3   329.9 1411.46   344.7  1418.1
#Mann= 6 ,-1,0
       0     .05       0      10     .08       0     100     .05       0
   156.1    .045       0  165.34     .05       0     300      .1       0
Bank Sta=156.1,165.34
XS Rating Curve= 0 ,0
Exp/Cntr(USF)=0,0
Exp/Cntr=0.3,0.1

Type RM Length L Ch R = 1 ,4443    ,77.3,75.9,74.1
XS GIS Cut Line= 2
2169851.21674962721911.1084656882169863.93910764721566.626156237
#Sta/Elev= 30
       0 1402.04    18.2 1401.87    21.9 1401.44    29.9 1399.01    33.7 1398.44
      46  1397.8      66 1392.65      90 1385.33      98 1383.81     110 1382.82
     130 1382.75     134 1383.59     138  1383.7     142 1382.74     154 1382.06
  159.441379.914     162 1378.79     166 1378.56  169.191379.876     174 1382.14
   178.1 1382.84   186.1 1383.66   206.1 1387.35   226.1 1390.03   242.1 1391.22
   271.2 1396.52   294.1 1402.65   302.1 1403.69   308.6 1405.19   344.7 1419.37
#Mann= 6 ,-1,0
       0     .05       0      10     .08       0     110     .05       0
  159.44    .045       0  169.19     .05       0     300      .1       0
Bank Sta=159.44,169.19
XS Rating Curve= 0 ,0
Exp/Cntr(USF)=0,0
Exp/Cntr=0.3,0.1

Type RM Length L Ch R = 1 ,4368    ,114.7,114.4,114
XS GIS Cut Line= 3
2169952.42426031 721897.057399882169922.12319368721666.011766864
2169879.70170041721573.593513658
#Sta/Elev= 30
       0 1409.59      20 1406.49    36.2 1405.72    40.2 1404.75    44.3 1403.24
    48.3 1401.09    56.4  1395.6    68.5  1388.8    72.5 1386.81    76.5  1385.4
   112.8 1382.66     137  1382.5   153.5 1381.73   157.2 1381.39   163.21379.008
   165.3 1378.14   169.3 1377.88   173.51378.983   177.4 1381.07   181.4 1382.39
   221.2  1383.3   244.2    1388   256.2 1389.08   260.3 1390.45   274.3 1397.46
   295.2 1406.37   308.8 1408.56   320.2 1411.78   328.6 1413.49   334.7 1415.85
#Mann= 5 ,-1,0
       0     .07       0   163.2    .045       0   173.5     .07       0
     190     .05       0  293.02      .1       0
Bank Sta=163.2,173.5
XS Rating Curve= 0 ,0
Exp/Cntr(USF)=0,0
Exp/Cntr=0.3,0.1

Type RM Length L Ch R = 1 ,4253    ,154,154.2,154.3
XS GIS Cut Line= 3
2170064.24852006721839.6502146442170016.68647392721550.754823309
2169984.09766453721517.285235289
#Sta/Elev= 30
       0 1402.89    22.8 1395.39      39 1389.47      43 1388.23    59.3 1385.22
    68.3  1383.2    75.5 1382.18    83.6 1381.71   103.9 1381.71   120.1 1381.15
  126.931378.528   128.2 1378.01   132.2 1377.37   136.3 1378.02     138 1378.56
   140.3 1379.25   152.5 1380.77   169.3 1381.76     193 1381.94   217.4 1381.48
   229.5 1381.64   245.7  1382.4   253.8 1383.33     262 1384.71   270.1 1384.99
   282.2 1388.26   294.3 1391.97   308.4 1397.29     331 1406.78   339.5  1409.9
#Mann= 5 ,-1,0
       0     .06       0      30     .05       0  126.93    .045       0
     138     .05       0  292.78      .1       0
Bank Sta=126.93,138
XS Rating Curve= 0 ,0
Exp/Cntr(USF)=0,0
Exp/Cntr=0.3,0.1

Type RM Length L Ch R = 1 ,4099    ,118.1,115.1,110.6
XS GIS Cut Line= 3
2170211.49837995 721800.093986682170178.92473333721583.441360311
2170022.87424021721520.566647064
#Sta/Elev= 30
       0 1408.91       7 1407.52      11 1406.29    19.1 1403.43    23.3 1401.52
    39.4  1396.6    59.6 1387.36    67.7 1382.69    71.7 1381.49    79.8 1380.97
   104.1    1381   108.1  1380.1   116.2  1377.5   128.3 1376.69   135.6 1377.36
   140.5 1378.11   148.6  1380.5   152.6 1381.05     189 1381.16   219.1 1382.44
   273.8 1383.93   282.4 1386.04   286.7 1385.89   299.7 1384.09     304 1383.86
   332.2 1384.82   342.8  1385.9   355.7 1388.59   381.6 1395.76   387.3 1397.79
#Mann= 3 ,-1,0
       0     .05       0   116.2    .045       0   135.6     .05       0
Bank Sta=116.2,135.6
XS Rating Curve= 0 ,0
Exp/Cntr(USF)=0,0
Exp/Cntr=0.3,0.1

Type RM Length L Ch R = 1 ,3984    ,81.3,73.4,63.2
XS GIS Cut Line= 3
2170341.79296644 721746.30959342 2170274.3730932721605.409633614
2170038.02477352721498.598373761
#Sta/Elev= 30
       0 1409.39      13 1409.07    14.6 1408.88      19 1407.59    31.6 1400.41
    41.2 1392.66      47 1388.88    54.5 1384.43      59 1382.06      71 1376.77
    76.6 1375.31    81.1 1375.18    85.5 1375.76      89 1376.68   103.2 1379.01
   107.7 1380.08   112.1 1380.55   156.2 1380.35   176.2 1381.19   211.3 1381.52
   263.6 1383.46   321.9 1383.48   329.8  1383.6   342.5 1384.73   348.5 1384.12
   360.6 1384.69   373.7 1386.08   382.5 1387.94   399.6 1393.24   415.6 1399.29
#Mann= 4 ,-1,0
       0     .06       0      40     .05       0      71    .045       0
      89     .05       0
#XS Ineff= 2 , 0
                          179.15         1386.92
Permanent Ineff=
       F       F
Bank Sta=71,89
XS Rating Curve= 0 ,0
Exp/Cntr(USF)=0,0
Exp/Cntr=0.3,0.1

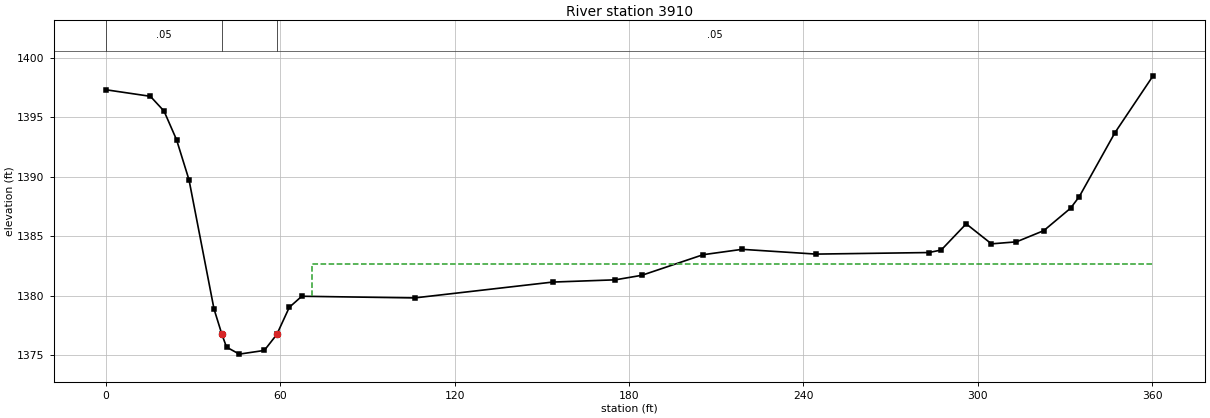
Type RM Length L Ch R = 1 ,3910    ,86.8,79.7,71.9
XS GIS Cut Line= 2
2170382.69940638721626.6203802512170048.63014684 721491.78063377
#Sta/Elev= 30
       0  1397.3    15.3 1396.75      20 1395.51    24.3 1393.11    28.6 1389.73
    37.2 1378.89    39.9 1376.77    41.5 1375.69    45.9  1375.1    54.5 1375.41
    58.8 1376.75    63.1 1379.03    67.4 1379.96   106.2 1379.82   153.7 1381.15
   175.3 1381.34   184.4 1381.72   205.5 1383.45   218.9  1383.9   244.3  1383.5
   283.1 1383.63   287.4 1383.84     296 1386.04   304.7 1384.36   313.3 1384.53
   322.7 1385.47   331.9 1387.35   334.9 1388.32   347.2  1393.7   360.3 1398.47
#Mann= 3 ,-1,0
       0     .05       0    39.9    .045       0    58.8     .05       0
#XS Ineff= 2 , 0
                           70.99          1382.7
Permanent Ineff=
       F       F
Bank Sta=39.9,58.8
XS Rating Curve= 0 ,0
Exp/Cntr(USF)=0,0
Exp/Cntr=0.3,0.1