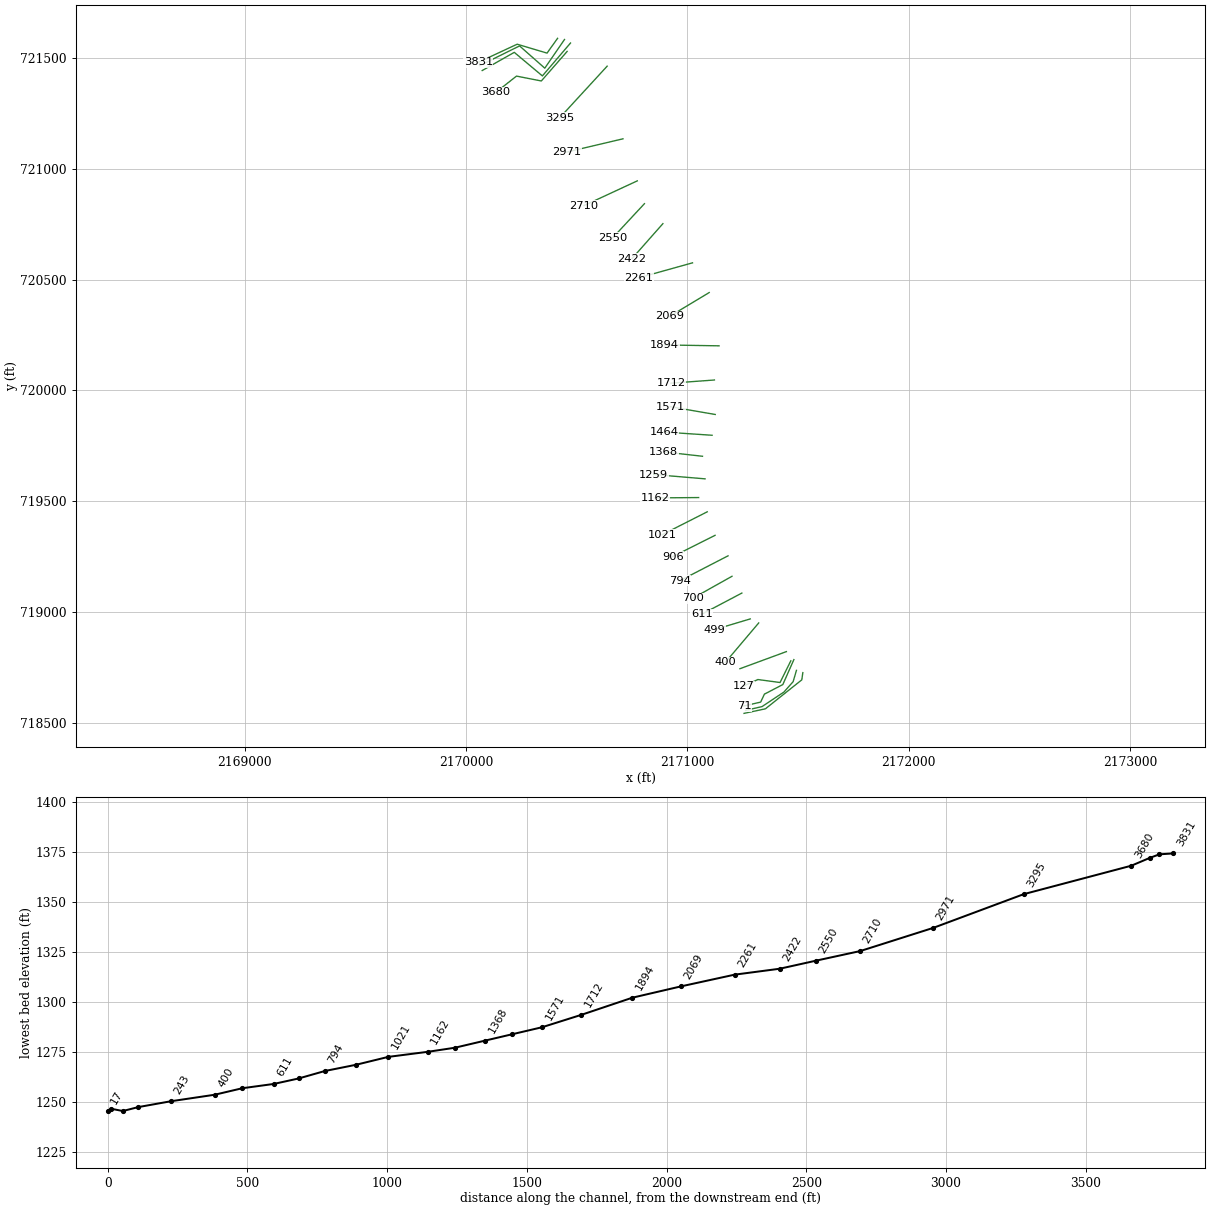
HEC-RAS study SPRUCEFK.prj: SPRUCEFK

--- SPRUCEFK.g01 (geometry) --- (continued)

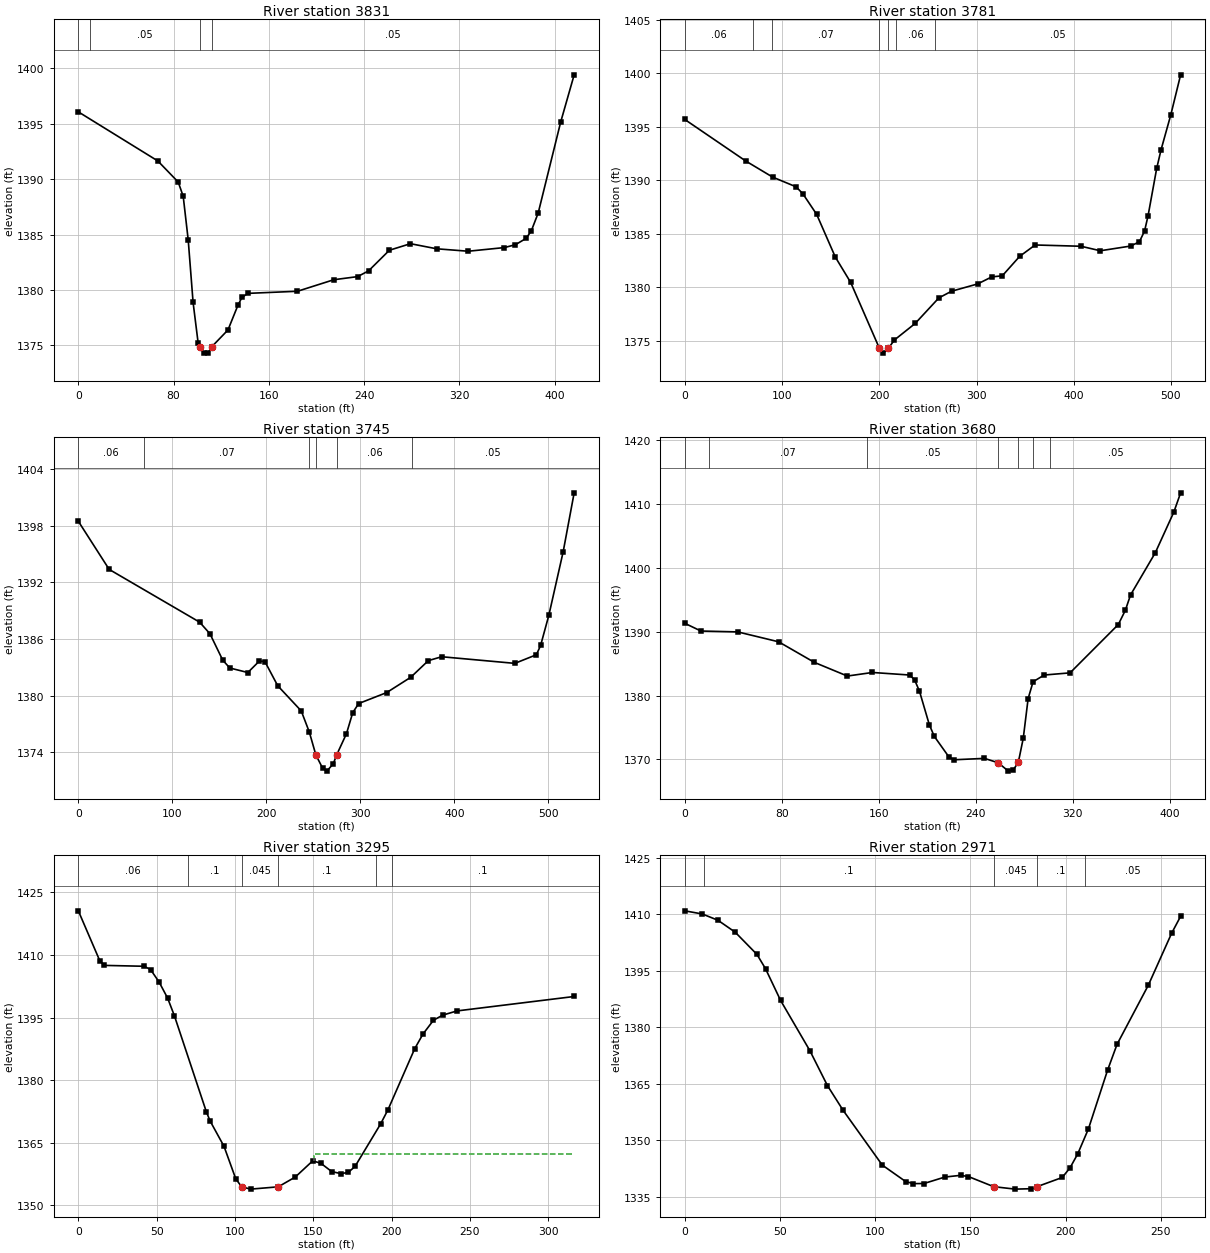
Type RM Length L Ch R = 1 ,3831    ,54.4,50.2,46.1
XS GIS Cut Line= 4
2170413.75799967 721588.744046972170366.03381974721522.081700395
2170231.19407326721562.2306136732170055.44788683721480.417733786
#Sta/Elev= 30
       0 1396.07    66.8 1391.64    83.9 1389.74    88.1 1388.45    92.3 1384.52
    96.4 1378.88   100.6 1375.26     102  1374.9   105.3 1374.31     109 1374.32
     1121374.876   125.7  1376.4     134 1378.61   137.4 1379.33   142.4  1379.7
   184.1 1379.89   214.6 1380.93   234.6 1381.21   243.8 1381.73   261.3 1383.59
     279 1384.18     301 1383.72   327.5  1383.5   357.9 1383.83   367.2 1384.09
     376 1384.65   380.4 1385.31   386.3 1386.95   405.2 1395.16   416.5 1399.41
#Mann= 4 ,-1,0
       0     .06       0      10     .05       0     102    .045       0
     112     .05       0
Bank Sta=102,112
XS Rating Curve= 0 ,0
Exp/Cntr(USF)=0,0
Exp/Cntr=0.3,0.1

Type RM Length L Ch R = 1 ,3781    ,34.9,35.3,37.6
XS GIS Cut Line= 4
2170445.01782177721583.5795943812170355.94840968721454.014365937
2170241.98180428721554.5669761222170062.14335039721465.467179814
#Sta/Elev= 30
       0 1395.67    62.7 1391.79    90.3 1390.29   114.5 1389.38   121.5 1388.72
   135.6 1386.81   154.8 1382.82   170.6 1380.45  200.171374.292   204.3 1373.85
   209.4 1374.31   215.6 1375.08   236.9 1376.62   261.3 1379.01   274.3 1379.63
   301.1 1380.31   315.7 1380.97   326.5 1381.07   344.4 1382.89   360.3 1383.95
   407.5 1383.83   427.3 1383.41   458.5 1383.85   467.5 1384.25   472.8 1385.25
   476.4 1386.67   485.3 1391.11   489.8 1392.85   499.7 1396.07   509.9 1399.84
#Mann= 7 ,-1,0
       0     .06       0      70     .05       0      90     .07       0
  200.17    .045       0   209.4     .07       0  217.23     .06       0
  257.23     .05       0
Bank Sta=200.17,209.4
XS Rating Curve= 0 ,0
Exp/Cntr(USF)=0,0
Exp/Cntr=0.3,0.1

Type RM Length L Ch R = 1 ,3745    ,57.6,65.3,73.7
XS GIS Cut Line= 4
2170472.06468481721567.5458023952170345.07402163721419.152218456
2170218.08335845721525.4533915662170073.25692797721443.408861984
#Sta/Elev= 30
       0 1398.45    32.8 1393.36     129 1387.78     140 1386.55   153.6 1383.76
   161.1 1382.93   180.3 1382.45   192.6 1383.67   198.5  1383.6   212.1 1381.05
   237.1 1378.39   245.7 1376.15  252.671373.727   259.9 1372.32   264.3 1372.02
   271.2  1372.8   274.7 1373.72   285.2 1375.98   291.9 1378.21   298.2 1379.17
     328 1380.33   353.6 1381.95   372.3 1383.71   386.5 1384.12   464.3 1383.42
   487.2 1384.33   491.7 1385.31   500.5 1388.52   515.7 1395.22   527.4 1401.46
#Mann= 6 ,-1,0
       0     .06       0      70     .07       0  245.31     .06       0
  252.67    .045       0   274.7     .06       0  355.31     .05       0
Bank Sta=252.67,274.7
XS Rating Curve= 0 ,0
Exp/Cntr(USF)=0,0
Exp/Cntr=0.3,0.1

Type RM Length L Ch R = 1 ,3680    ,364.2,384.8,394.2
XS GIS Cut Line= 4
2170456.93701961721529.6569670512170340.27791311721396.332273901
2170228.16396659721418.3005472042170135.74571339721345.577987304
#Sta/Elev= 30
       0 1391.33    13.3 1390.12    43.7 1389.98    77.4 1388.43   106.9  1385.2
   134.1 1383.06   154.8 1383.62   185.4 1383.22   189.5 1382.48   193.6 1380.67
   201.7 1375.43   205.8  1373.6     218 1370.34   222.1 1369.93   247.2 1370.15
   258.61369.453   266.9 1368.15     271 1368.37   275.1 1369.51   279.2 1373.32
   283.2 1379.51   287.3 1382.17   296.5 1383.22   317.8 1383.56   357.6 1391.14
   363.4 1393.37   367.7 1395.78   388.1 1402.39   403.4 1408.77     409 1411.79
#Mann= 7 ,-1,0
       0     .06       0      20     .07       0     150     .05       0
   258.6    .045       0   275.1     .05       0  287.16     .06       0
   301.4     .05       0
Bank Sta=258.6,275.1
XS Rating Curve= 0 ,0
Exp/Cntr(USF)=0,0
Exp/Cntr=0.3,0.1

Type RM Length L Ch R = 1 ,3295    ,327.9,323.9,309.2
XS GIS Cut Line= 2
2170637.66183272721463.0981789842170423.33903224721230.181162935
#Sta/Elev= 30
       0 1420.57    13.7 1408.61    16.6  1407.5      42 1407.29    46.1  1406.5
    51.5 1403.55      57 1399.66    61.3 1395.46    81.7 1372.45    84.1 1370.24
      93 1364.15   100.5 1356.37  104.25 1354.46     110 1353.91   127.6 1354.46
   138.5 1356.81   149.6 1360.68   154.8 1360.11   161.7 1358.12   167.6 1357.62
   172.3 1357.91   176.6 1359.33   192.9 1369.49   197.7 1372.96   214.7 1387.53
     220 1391.06   226.7 1394.36   232.6 1395.59   241.8  1396.6   316.5 1400.05
#Mann= 6 ,-1,0
       0     .06       0      70      .1       0  104.25    .045       0
   127.6      .1       0     190     .07       0     200      .1       0
#XS Ineff= 2 , 0
                          150.18         1362.36
Permanent Ineff=
       F       F
Bank Sta=104.25,127.6
XS Rating Curve= 0 ,0
Exp/Cntr(USF)=0,0
Exp/Cntr=0.3,0.1

Type RM Length L Ch R = 1 ,2971    ,253,261.1,261.4
XS GIS Cut Line= 2
2170709.10276621721135.2527992512170455.63424875721075.555580852
#Sta/Elev= 30
       0 1410.93     9.2 1410.09    17.4 1408.43    26.5 1405.24    37.9 1399.35
    42.4 1395.55    50.3 1387.14    65.7 1373.78    74.9 1364.53    83.1 1357.98
   103.7 1343.41     116 1339.03   120.1 1338.48   125.6 1338.51   136.6 1340.23
   144.8 1340.68   148.9 1340.37  162.211337.675   173.5 1337.02   181.8 1337.13
  185.111337.695   198.2 1340.11   202.3 1342.66   206.4 1346.42     212 1353.05
     222 1368.56     227 1375.46   243.4 1391.14   255.7    1405   260.4 1409.48
#Mann= 5 ,-1,0
       0     .06       0      10      .1       0  162.21    .045       0
  185.11      .1       0     210     .05       0
Bank Sta=162.21,185.11
XS Rating Curve= 0 ,0
Exp/Cntr(USF)=0,0
Exp/Cntr=0.3,0.1

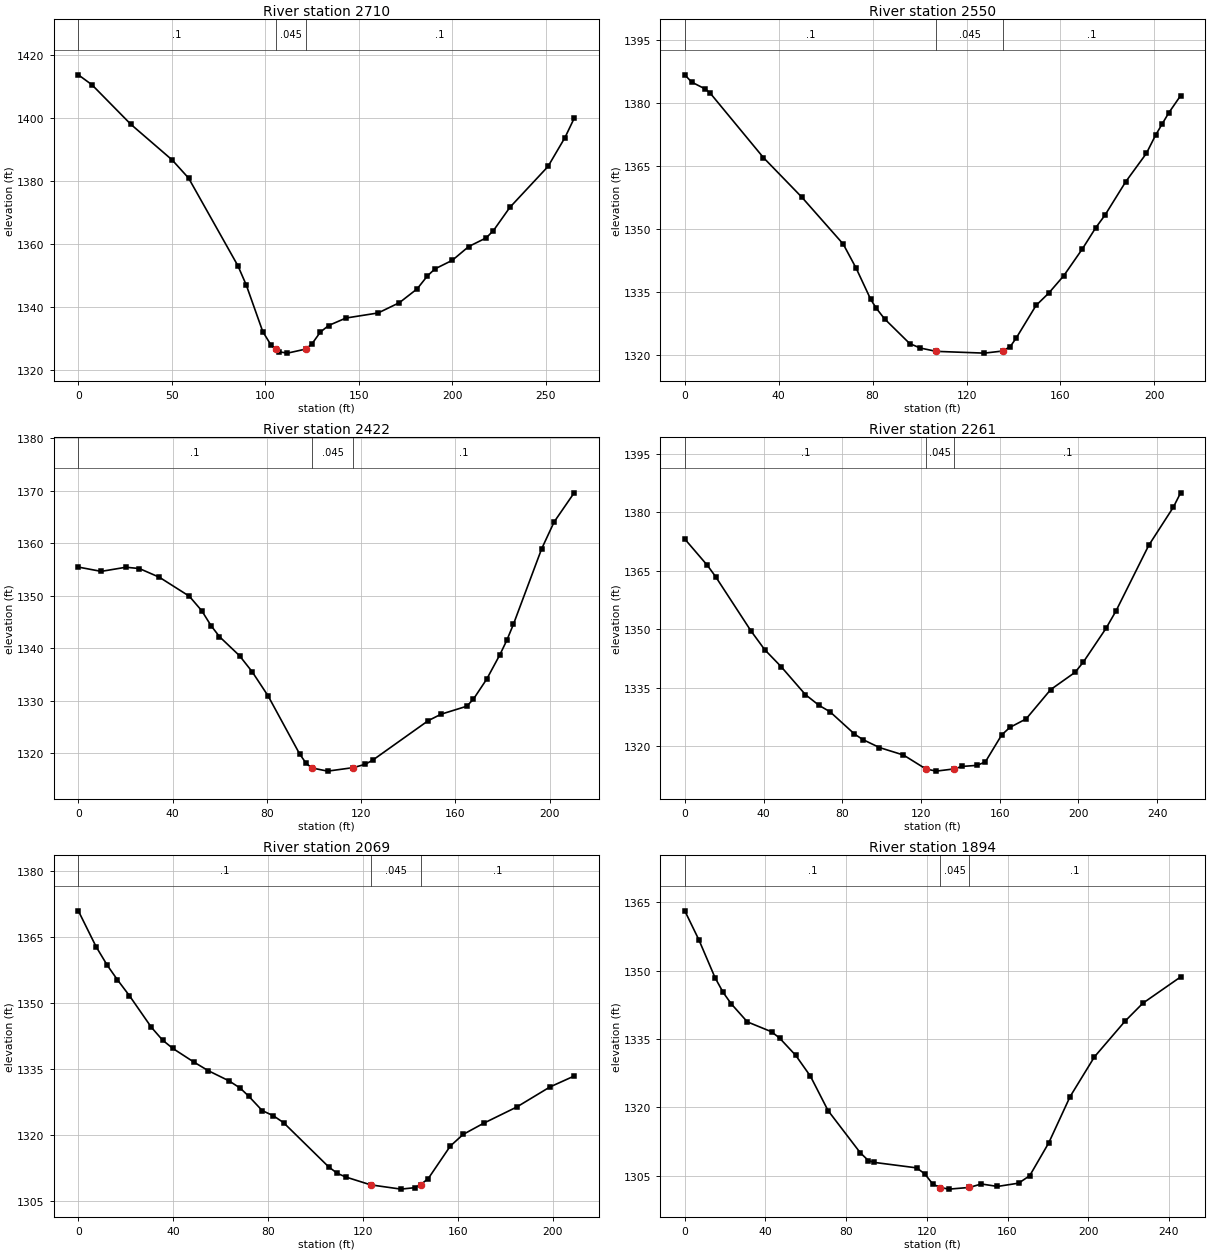
Type RM Length L Ch R = 1 ,2710    ,154.2,160.1,167.2
XS GIS Cut Line= 2
2170773.69319923720945.3960718832170532.94703979720833.830778481
#Sta/Elev= 30
       0 1413.83     7.3 1410.66    28.1 1398.11    50.2 1386.79      59 1381.02
    85.4 1353.15    89.8 1347.14    98.7 1332.24   103.1 1327.98  105.641326.609
   107.5 1325.83   111.9 1325.42   121.8 1326.72   125.1 1328.44   129.5  1332.1
   133.9 1334.19   143.2 1336.57   160.4 1338.18   171.8 1341.45   181.3 1345.84
   186.8 1349.96   190.8 1352.17   200.1 1354.91   208.9 1359.29   218.2 1362.02
   222.1 1364.34   230.9 1371.72   251.3 1384.71   260.4 1393.92   265.3 1400.01
#Mann= 3 ,-1,0
       0      .1       0  105.64    .045       0   121.8      .1       0
Bank Sta=105.64,121.8
XS Rating Curve= 0 ,0
Exp/Cntr(USF)=0,0
Exp/Cntr=0.3,0.1

Type RM Length L Ch R = 1 ,2550    ,127.1,128.3,127.5
XS GIS Cut Line= 2
2170806.15681247720842.580281329  2170662.226746720688.044841541
#Sta/Elev= 30
       0 1386.69     2.9 1384.97     8.8  1383.3    10.9 1382.28    33.5 1367.01
    49.9 1357.58    67.5 1346.45      73 1340.72    79.2 1333.31    81.6 1331.19
    85.1 1328.69    95.8 1322.82   100.3 1321.76   107.1 1320.97   127.6 1320.55
   135.4 1321.05   138.6 1322.09   141.1 1324.07   149.6 1331.87     155  1334.8
   161.4 1338.93   169.4 1345.36     175 1350.32     179 1353.36   187.8 1361.27
   196.6 1368.01   200.5 1372.31   203.3 1374.98   206.2  1377.7   211.2 1381.74
#Mann= 3 ,-1,0
       0      .1       0   107.1    .045       0   135.4      .1       0
Bank Sta=107.1,135.4
XS Rating Curve= 0 ,0
Exp/Cntr(USF)=0,0
Exp/Cntr=0.3,0.1

Type RM Length L Ch R = 1 ,2422    ,166.8,161.1,151.3
XS GIS Cut Line= 2
2170889.48474569 720752.434608122170750.09983921 720594.86906167
#Sta/Elev= 30
       0 1355.47     9.7 1354.65    20.2 1355.44    25.9 1355.19    34.4 1353.53
    47.1 1349.91    52.4 1347.13    56.3 1344.31    59.9  1342.2    68.4 1338.57
    73.8 1335.49    80.5 1330.92    93.9 1319.84    96.7 1318.03    99.11317.165
   105.8 1316.56   116.7 1317.23   121.8 1317.87   125.1 1318.71   148.5 1326.19
   153.9 1327.41   164.8 1328.93   167.6 1330.25   173.3 1334.11   178.9 1338.77
   181.8 1341.49   184.6 1344.53   196.6 1358.95   201.9 1364.08   210.4 1369.63
#Mann= 3 ,-1,0
       0      .1       0    99.1    .045       0   116.7      .1       0
Bank Sta=99.1,116.7
XS Rating Curve= 0 ,0
Exp/Cntr(USF)=0,0
Exp/Cntr=0.3,0.1

Type RM Length L Ch R = 1 ,2261    ,187.9,191.4,194.6
XS GIS Cut Line= 2
  2171023.247145720575.4690463932170780.54369971720507.942684597
#Sta/Elev= 30
       0 1373.15    11.5 1366.38    15.6 1363.54    33.6 1349.59    40.6 1344.76
    48.9 1340.43    61.3 1333.22    68.2 1330.48    73.8 1328.82    86.2 1323.12
    90.4 1321.71    98.9 1319.65   111.1 1317.73  122.421314.171   127.7  1313.6
  136.781314.167   140.8  1314.8   148.5 1315.08   152.7 1315.97     161 1322.89
   165.1  1324.8   173.4    1327   185.9 1334.53   198.3 1338.96   202.5  1341.6
     214 1350.24   219.1 1354.73   235.7 1371.53   248.2 1381.32   251.9 1385.01
#Mann= 3 ,-1,0
       0      .1       0  122.42    .045       0  136.78      .1       0
Bank Sta=122.42,136.78
XS Rating Curve= 0 ,0
Exp/Cntr(USF)=0,0
Exp/Cntr=0.3,0.1

Type RM Length L Ch R = 1 ,2069    ,182.5,174.7,166
XS GIS Cut Line= 2
2171098.60265019720441.394965726  2170919.510995720333.744244022
#Sta/Elev= 30
       0    1371     7.5 1362.84    12.2 1358.62    16.5 1355.31    21.5 1351.74
    30.8 1344.52    35.5 1341.62    39.8 1339.74    48.6 1336.66    54.8 1334.66
    63.5 1332.36    68.2 1330.72    71.9 1328.83    77.5  1325.6    82.2 1324.43
    86.5 1322.86   105.5 1312.82   109.1 1311.36   112.7 1310.51  123.221308.723
     136 1307.75   141.8 1308.08  144.23 1308.75   147.5 1310.15   156.8 1317.54
   162.2 1320.18   170.8 1322.71   184.8 1326.41   198.8 1330.97     209 1333.45
#Mann= 3 ,-1,0
       0      .1       0  123.22    .045       0  144.23      .1       0
Bank Sta=123.22,144.23
XS Rating Curve= 0 ,0
Exp/Cntr(USF)=0,0
Exp/Cntr=0.3,0.1

Type RM Length L Ch R = 1 ,1894    ,184.4,182.6,180.4
XS GIS Cut Line= 2
2171143.19940827720200.9521855872170897.46216991720204.915689431
#Sta/Elev= 30
       0 1363.11       7 1356.73      15 1348.44      19 1345.22      23 1342.72
      31 1338.75      43 1336.58      47 1335.19      55  1331.4    62.3 1326.82
      71  1319.3      87 1310.03      91 1308.33    93.8 1307.93     115 1306.72
     119 1305.38     123 1303.14  126.711302.407     131 1302.06  141.09 1302.43
     147 1303.19     155 1302.65   165.5 1303.37     171 1305.01   180.4 1312.19
     191 1322.35   203.1 1331.09   218.3 1338.93   227.1 1342.85   245.8 1348.61
#Mann= 3 ,-1,0
       0      .1       0  126.71    .045       0  141.09      .1       0
Bank Sta=126.71,141.09
XS Rating Curve= 0 ,0
Exp/Cntr(USF)=0,0
Exp/Cntr=0.3,0.1

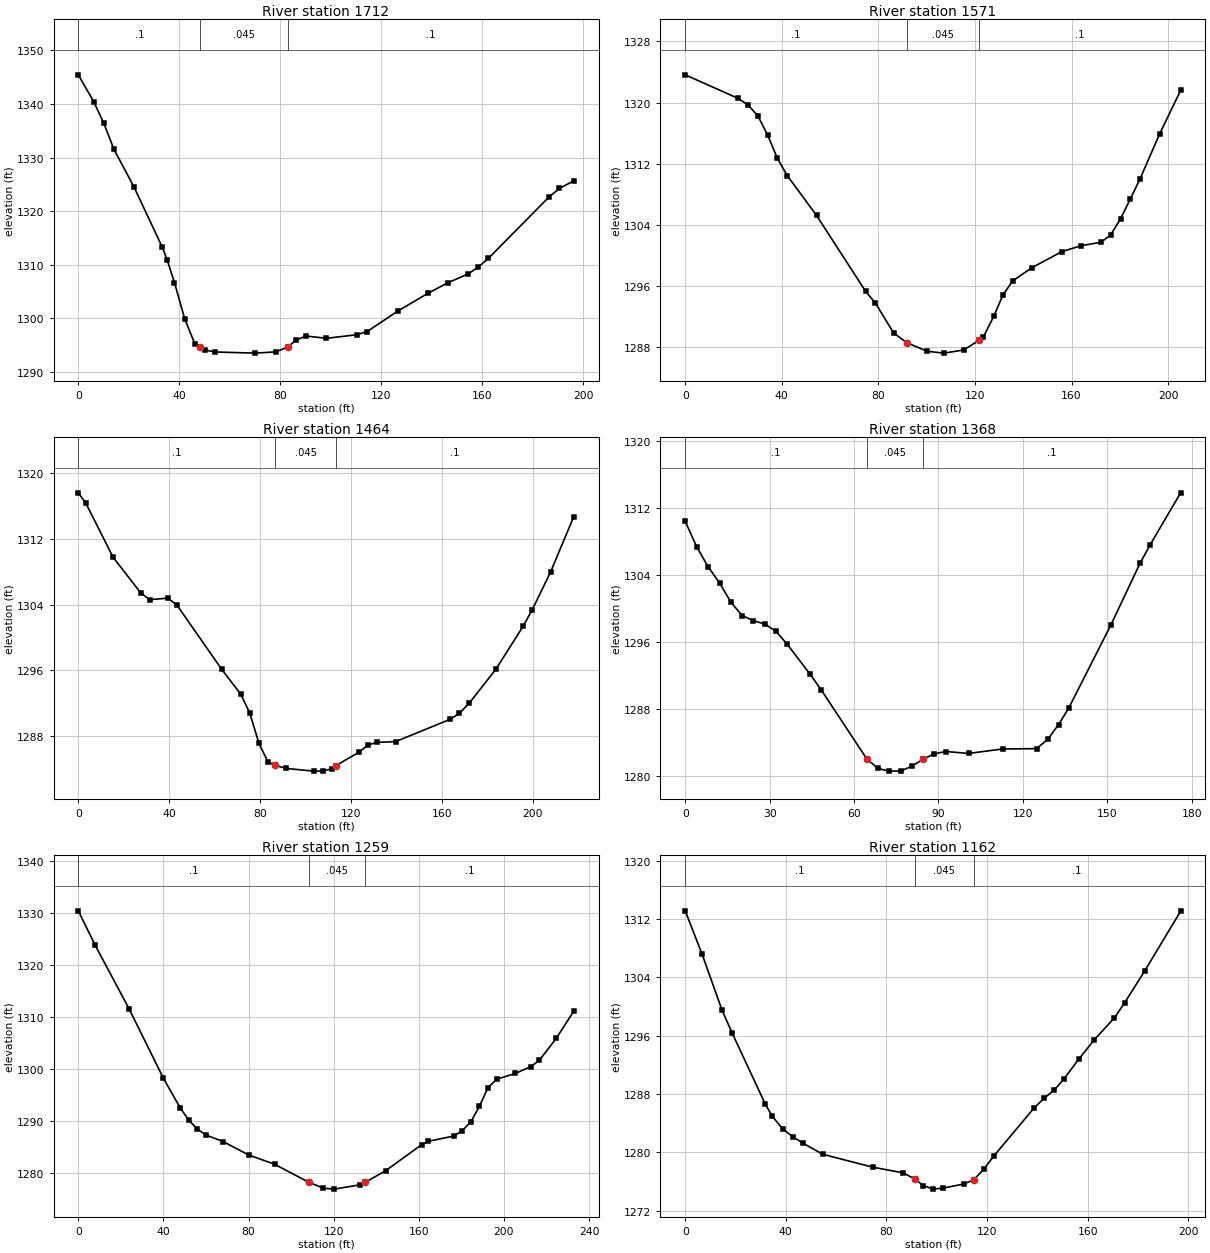
Type RM Length L Ch R = 1 ,1712    ,145.1,141,133.7
XS GIS Cut Line= 2
2171122.22358661720046.7121404882170926.42649669720032.443526647
#Sta/Elev= 30
       0 1345.45     6.1 1340.44    10.1 1336.41    14.1 1331.56    22.1 1324.46
    33.3 1313.23    35.2 1310.87    38.1 1306.64    42.2  1299.8    46.2 1295.18
   48.321294.586    50.2 1294.06    54.2 1293.68    70.2 1293.47    78.3 1293.71
   83.041294.626    86.3 1295.93    90.3 1296.66    98.3 1296.24   110.3  1296.9
   114.4 1297.49   126.7 1301.36   138.4 1304.61   146.4 1306.61   154.5 1308.27
   158.5 1309.56   162.5 1311.18   186.5 1322.64   190.6 1324.22   196.3 1325.66
#Mann= 3 ,-1,0
       0      .1       0   48.32    .045       0   83.04      .1       0
Bank Sta=48.32,83.04
XS Rating Curve= 0 ,0
Exp/Cntr(USF)=0,0
Exp/Cntr=0.3,0.1

Type RM Length L Ch R = 1 ,1571    ,103.8,106.6,107.9
XS GIS Cut Line= 2
2171125.83306536719891.1267893042170923.57344564719925.973015922
#Sta/Elev= 30
       0 1323.63      22 1320.54      26 1319.69    30.1 1318.27    34.2 1315.72
    38.2  1312.7    42.3 1310.44    54.4 1305.25    74.7 1295.34    78.8 1293.79
    86.3  1289.9    91.71288.627   100.2 1287.49   107.2 1287.25   115.3 1287.66
   121.81288.935   123.5 1289.36   127.9 1292.13   131.6 1294.85   135.6 1296.68
   143.7 1298.44   155.9  1300.5     164  1301.3   172.2 1301.74   176.2  1302.7
   180.3 1304.81   184.3 1307.36   188.4 1310.04   196.5 1315.91   205.2  1321.6
#Mann= 3 ,-1,0
       0      .1       0    91.7    .045       0   121.8      .1       0
Bank Sta=91.7,121.8
XS Rating Curve= 0 ,0
Exp/Cntr(USF)=0,0
Exp/Cntr=0.3,0.1

Type RM Length L Ch R = 1 ,1464    ,96.1,96.1,94.4
XS GIS Cut Line= 2
2171111.46697185719797.3364043892170893.99076639719811.834818086
#Sta/Elev= 30
       0 1317.58     3.3 1316.33    15.3 1309.75    27.4 1305.44    31.4 1304.59
    39.4 1304.78    43.4 1303.93    63.1 1296.12    71.5  1293.1    75.5 1290.76
    79.5 1287.11    83.5 1284.84   86.681284.458    91.5 1284.08   103.5 1283.75
   107.5 1283.75   111.5 1284.04  113.351284.419   123.6 1286.07   127.6 1286.95
   131.6 1287.25   139.6 1287.34   163.7 1290.06   167.7 1290.78   172.1 1292.04
   183.7 1296.13   195.7 1301.35   199.7 1303.35   207.8 1307.96     218 1314.69
#Mann= 3 ,-1,0
       0      .1       0   86.68    .045       0  113.35      .1       0
Bank Sta=86.68,113.35
XS Rating Curve= 0 ,0
Exp/Cntr(USF)=0,0
Exp/Cntr=0.3,0.1

Type RM Length L Ch R = 1 ,1368    ,108.6,109,109.6
XS GIS Cut Line= 2
2171068.26103877719702.5026495632170893.27237901719722.198342869
#Sta/Elev= 30
       0 1310.38     4.1 1307.33     8.1 1304.98    12.2 1303.03    16.2 1300.76
    20.2 1299.14    24.2 1298.54    28.3 1298.12    32.3 1297.26    36.3  1295.7
    44.4 1292.14    48.4 1290.25    64.5 1282.07    68.5 1280.91    72.5 1280.59
    76.6 1280.61    80.6 1281.18    84.6 1282.02    88.6 1282.66    92.7 1282.93
   100.7  1282.7   112.8 1283.23   124.9 1283.27   128.9  1284.4   132.7 1286.13
   136.4 1288.16   151.3 1298.01   161.7 1305.39   165.3  1307.6   176.1 1313.77
#Mann= 3 ,-1,0
       0      .1       0    64.5    .045       0    84.6      .1       0
Bank Sta=64.5,84.6
XS Rating Curve= 0 ,0
Exp/Cntr(USF)=0,0
Exp/Cntr=0.3,0.1

Type RM Length L Ch R = 1 ,1259    ,95.7,96.9,98.6
XS GIS Cut Line= 2
2171080.02599829 719600.598896942170848.08762517719620.171755432
#Sta/Elev= 30
       0 1330.38     7.9 1323.79    23.9 1311.55      40 1298.25      48  1292.5
      52 1290.18      56 1288.49    60.1 1287.36    68.1 1286.11    80.1 1283.54
    92.2 1281.78   108.2 1278.33   115.2 1277.18   120.3    1277   132.3 1277.83
   134.91278.324   144.4 1280.53   161.4 1285.55   164.4 1286.17   176.5 1287.19
   180.5 1288.23   184.5 1289.95   188.5 1292.91   192.5 1296.47   196.6 1298.08
   205.3 1299.18   212.6  1300.5   216.6 1301.69   224.6 1305.94   232.8 1311.13
#Mann= 3 ,-1,0
       0      .1       0   108.2    .045       0   134.9      .1       0
Bank Sta=108.2,134.9
XS Rating Curve= 0 ,0
Exp/Cntr(USF)=0,0
Exp/Cntr=0.3,0.1

Type RM Length L Ch R = 1 ,1162    ,134.4,141.4,144.1
XS GIS Cut Line= 2
2171050.83792546719516.151089819 2170853.8809924719514.636036488
#Sta/Elev= 30
       0 1313.14     6.7 1307.21    14.7 1299.47    18.7 1296.35    31.9 1286.59
    34.7 1284.93    38.7 1283.24    42.7 1282.17    46.7 1281.29    54.7 1279.74
    74.7 1277.96    86.7 1277.19    91.41276.323    94.7 1275.44    98.7 1274.96
   102.7 1275.11   110.7 1275.66   114.7 1276.24   118.7 1277.67   122.7  1279.5
   138.7 1286.08   142.7 1287.43   146.7 1288.53   150.7 1290.12   156.4 1292.75
   162.7 1295.47   170.7 1298.47   174.7 1300.51   182.7 1304.89     197 1313.09
#Mann= 3 ,-1,0
       0      .1       0    91.4    .045       0   114.7      .1       0
Bank Sta=91.4,114.7
XS Rating Curve= 0 ,0
Exp/Cntr(USF)=0,0
Exp/Cntr=0.3,0.1

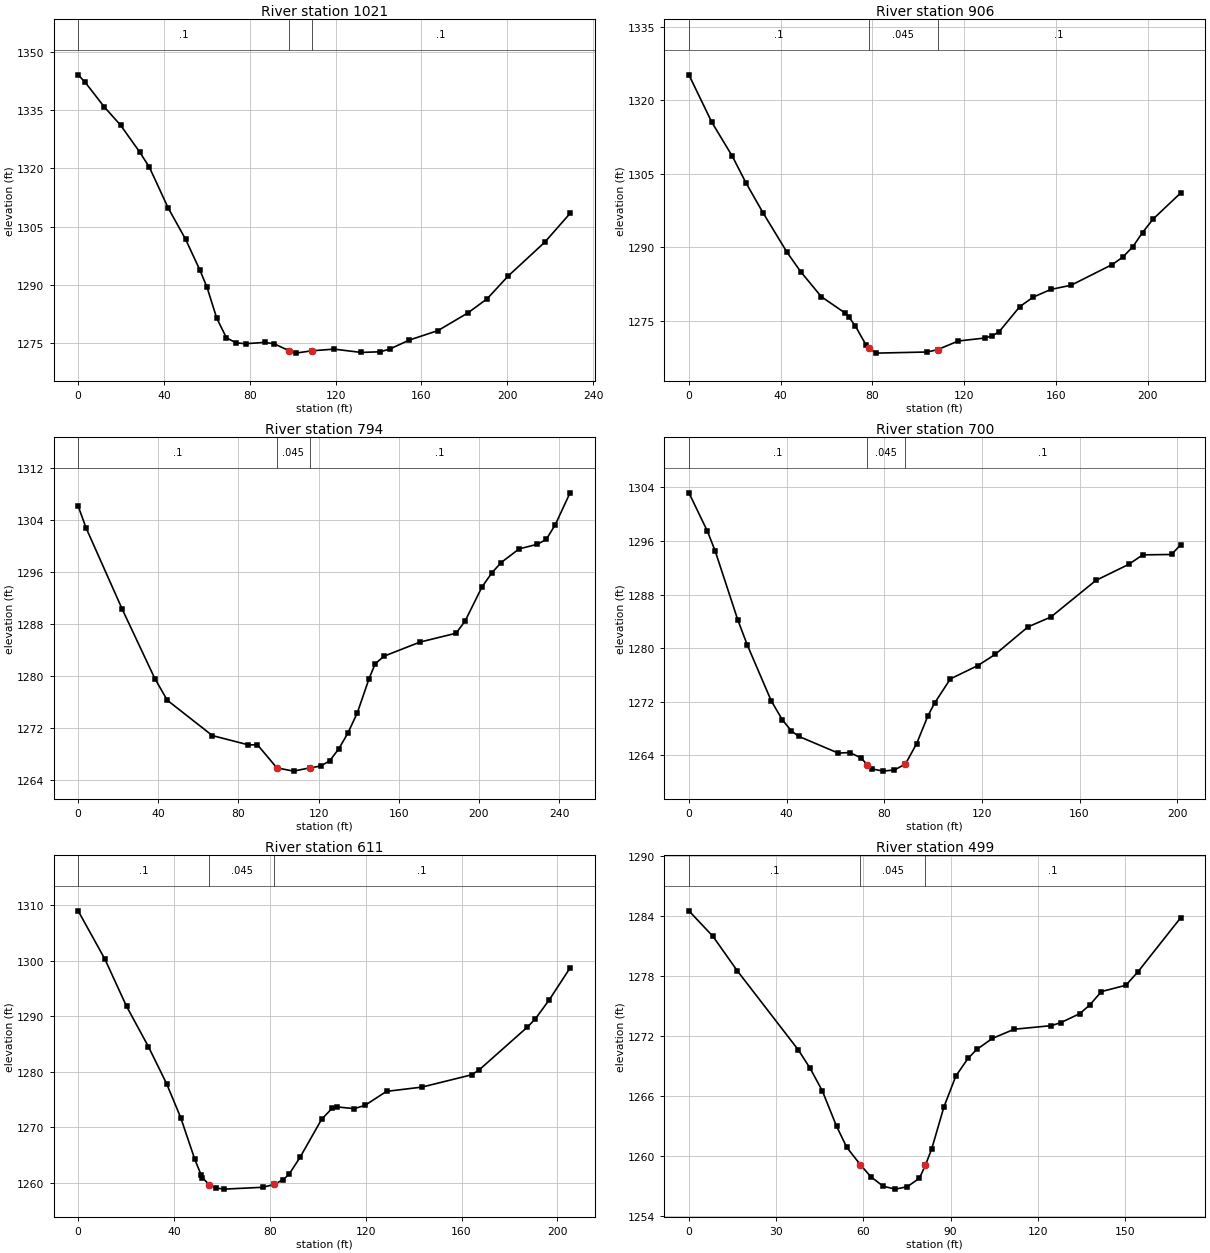
Type RM Length L Ch R = 1 ,1021    ,114.6,115.3,114.2
XS GIS Cut Line= 2
2171089.81242754719451.845172405 2170885.2760563719348.109022399
#Sta/Elev= 30
       0 1344.09     3.2 1342.22    12.1 1335.88    19.8 1331.11    28.7  1324.2
    33.2 1320.31    41.9 1309.88    50.1 1301.72    56.8 1293.75    60.1 1289.34
    64.6 1281.43    69.1 1276.39    73.6 1275.06    78.1 1274.85    87.1 1275.19
    91.5  1274.8    98.4 1273.01   101.4 1272.42  108.791273.015   119.3 1273.45
   131.9  1272.6   140.9 1272.77   145.4  1273.5   154.3 1275.77   167.8 1278.24
   181.7 1282.78   190.7 1286.44   200.4 1292.25   217.5 1300.98   229.3 1308.39
#Mann= 3 ,-1,0
       0      .1       0    98.4    .045       0  108.79      .1       0
Bank Sta=98.4,108.79
XS Rating Curve= 0 ,0
Exp/Cntr(USF)=0,0
Exp/Cntr=0.3,0.1

Type RM Length L Ch R = 1 ,906     ,110.8,111.7,111.9
XS GIS Cut Line= 2
 2171125.0755387719345.7075900532170933.42129229719249.501703519
#Sta/Elev= 30
       0 1325.18      10  1315.5    18.9 1308.61    24.9 1303.14    32.3 1297.07
    42.8 1288.99    48.7 1285.08    57.7 1279.98    68.1 1276.63    69.6 1275.92
    72.6 1273.95    77.1 1270.22    78.5 1269.52    81.6 1268.47   103.9  1268.7
   108.4 1269.18   117.4 1270.94   129.2 1271.56   132.2    1272   135.2 1272.82
   144.2 1277.94   150.1 1279.89   157.7 1281.44   166.6 1282.31   184.5 1286.52
     189 1287.99   193.5 1290.15   197.7 1293.04   202.4 1295.83   214.4 1301.13
#Mann= 3 ,-1,0
       0      .1       0    78.5    .045       0   108.4      .1       0
Bank Sta=78.5,108.4
XS Rating Curve= 0 ,0
Exp/Cntr(USF)=0,0
Exp/Cntr=0.3,0.1

Type RM Length L Ch R = 1 ,794     ,92.7,93.4,93.9
XS GIS Cut Line= 2
 2171183.7621483719253.1806587152170965.52477612719140.636722389
#Sta/Elev= 30
       0 1306.15       4 1302.76      22 1290.27    38.3 1279.58    44.5 1276.25
      67 1270.81      85 1269.38    89.5 1269.39   99.191265.839   107.5 1265.34
   115.5 1265.84   121.1 1266.12   125.6 1266.95   130.1 1268.78   134.6 1271.19
   139.3 1274.29   145.2 1279.58   148.2 1281.84   152.6 1283.03   170.6 1285.21
   188.6 1286.57   193.1 1288.43   201.6 1293.73   206.6 1295.91   211.1 1297.45
   220.1 1299.56   229.1 1300.26   233.6 1301.01   238.1 1303.26   245.5 1308.19
#Mann= 3 ,-1,0
       0      .1       0   99.19    .045       0   115.5      .1       0
Bank Sta=99.19,115.5
XS Rating Curve= 0 ,0
Exp/Cntr(USF)=0,0
Exp/Cntr=0.3,0.1

Type RM Length L Ch R = 1 ,700     ,89.1,89.3,87.3
XS GIS Cut Line= 2
2171201.58573192719160.871083641 2171025.8395455719062.392617109
#Sta/Elev= 30
       0  1303.2     7.6 1297.45    10.8 1294.47      20 1284.24    23.9 1280.48
    33.7 1272.14    38.3 1269.27      42 1267.63    44.9 1266.83    61.2 1264.31
    65.8  1264.4    70.4 1263.63      73  1262.6      75 1261.95    79.6 1261.62
    84.2  1261.8    88.7 1262.68    93.3 1265.74    97.9 1269.88   100.7 1271.82
   107.1  1275.4   118.4  1277.4   125.4 1279.05   138.9 1283.17   148.3 1284.65
   166.7 1290.11   180.1  1292.5   185.9 1293.93   197.7 1293.99   201.5 1295.47
#Mann= 3 ,-1,0
       0      .1       0      73    .045       0    88.7      .1       0
Bank Sta=73,88.7
XS Rating Curve= 0 ,0
Exp/Cntr(USF)=0,0
Exp/Cntr=0.3,0.1

Type RM Length L Ch R = 1 ,611     ,114.1,112.3,106.6
XS GIS Cut Line= 2
2171246.06908116719085.071551893 2171064.4764496 718989.38202149
#Sta/Elev= 30
       0 1308.95    11.2 1300.23    20.2 1291.77    29.3 1284.53    36.9 1277.86
    42.8 1271.75    48.7 1264.21    51.3 1261.46    51.9 1260.92    54.6  1259.7
    57.6 1259.08    60.9 1258.87      77  1259.2   81.771259.705    85.6 1260.57
      88 1261.53    92.6 1264.58   101.6 1271.42   106.1 1273.47   107.9 1273.67
   115.2 1273.35   119.7 1273.94   128.7 1276.46   143.5 1277.23   164.2 1279.44
   167.3  1280.3   187.5 1288.03   190.8  1289.5   196.6 1292.92   205.3 1298.66
#Mann= 3 ,-1,0
       0      .1       0    54.6    .045       0   81.77      .1       0
Bank Sta=54.6,81.77
XS Rating Curve= 0 ,0
Exp/Cntr(USF)=0,0
Exp/Cntr=0.3,0.1

Type RM Length L Ch R = 1 ,499     ,84.1,98.8,100.6
XS GIS Cut Line= 2
2171284.15613848718968.4593105722171122.04543203718919.977603972
#Sta/Elev= 30
       0 1284.51     8.3 1281.95    16.7  1278.5    37.6 1270.64    41.7 1268.79
    45.9 1266.53    50.8    1263    54.3  1260.9      59 1259.16    62.6 1257.96
    66.8 1257.02      71 1256.73    75.1 1256.97    79.3 1257.82    81.3 1259.09
    83.5 1260.73    87.7 1264.92    91.8 1268.01      96 1269.78      99 1270.67
   104.4 1271.78   111.9 1272.69   124.7 1273.05     128 1273.36   134.4 1274.24
   137.8 1275.09   141.9 1276.45   150.3 1277.08   154.5 1278.44   169.2 1283.84
#Mann= 3 ,-1,0
       0      .1       0      59    .045       0    81.3      .1       0
Bank Sta=59,81.3
XS Rating Curve= 0 ,0
Exp/Cntr(USF)=0,0
Exp/Cntr=0.3,0.1

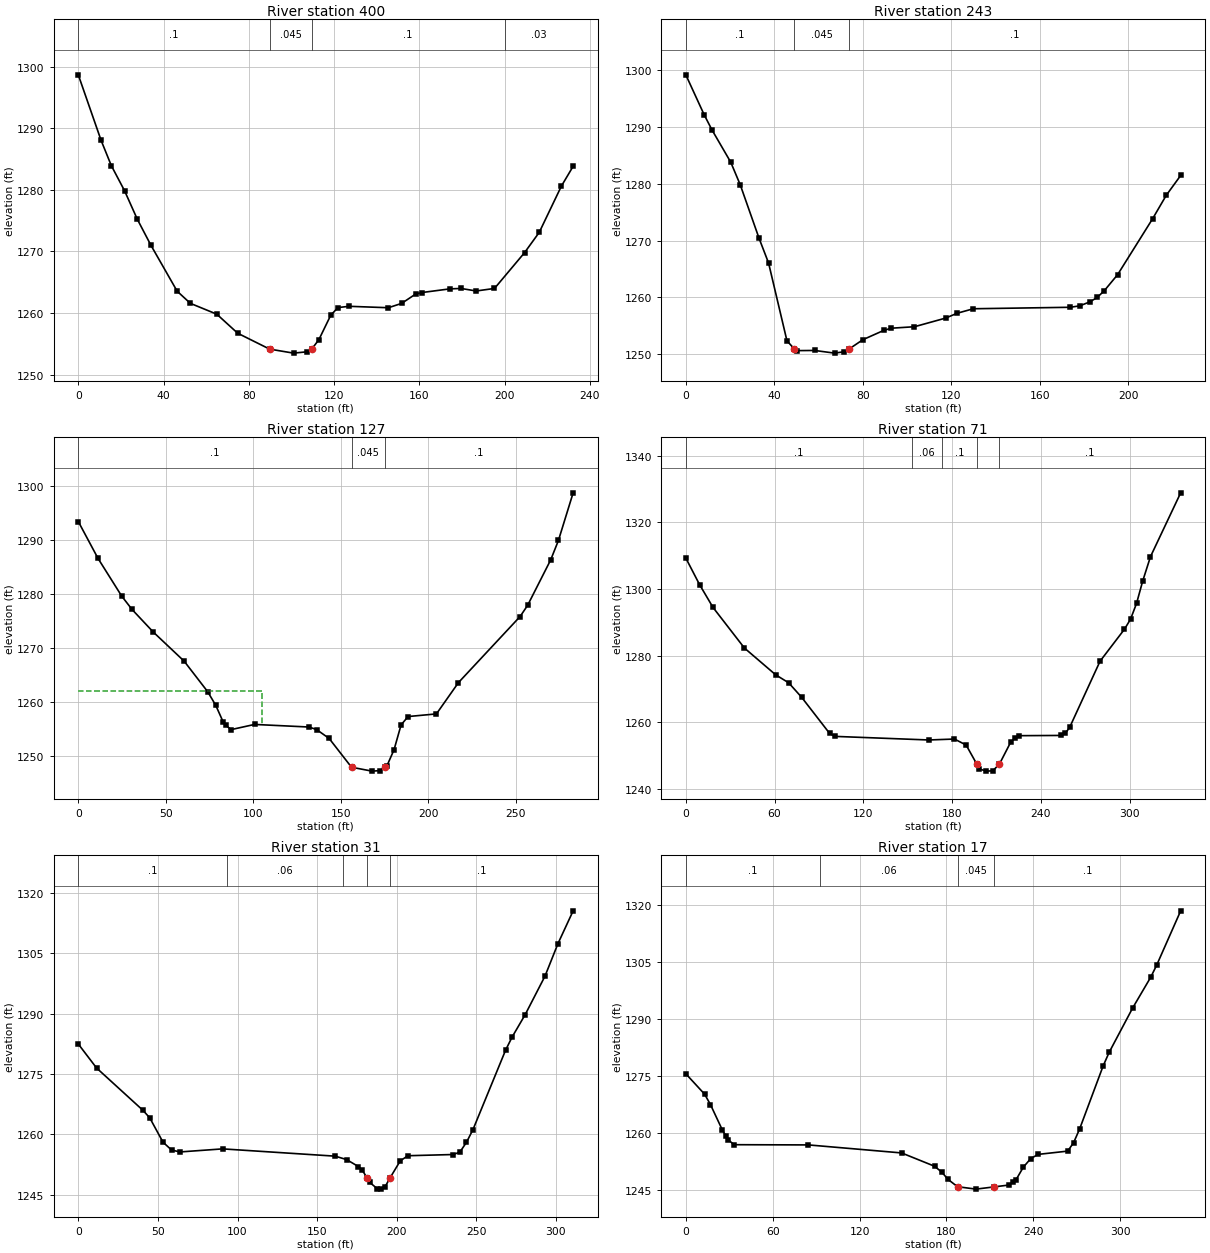
Type RM Length L Ch R = 1 ,400     ,167.2,156.8,148.6
XS GIS Cut Line= 2
2171322.18575307718950.236304507 2171172.1271713718772.993197056
#Sta/Elev= 30
       0 1298.65    10.7 1288.01    15.5 1283.91    21.7 1279.84    27.7  1275.2
    34.1 1270.97    46.4 1263.52    52.6 1261.55      65 1259.79    74.8  1256.7
    89.8 1254.12     101 1253.47   107.2 1253.68  109.481254.094   112.9 1255.66
   118.5 1259.65   121.9 1260.87   127.1 1261.07   145.5 1260.84   151.7 1261.54
   158.3 1263.06   161.1  1263.3   174.3  1263.9   179.6 1263.97   186.7 1263.56
   195.3 1263.97   209.4 1269.78   216.3 1273.08   226.7 1280.59   232.2  1283.8
#Mann= 4 ,-1,0
       0      .1       0    89.8    .045       0  109.48      .1       0
     200     .03       0
Bank Sta=89.8,109.48
XS Rating Curve= 0 ,0
Exp/Cntr(USF)=0,0
Exp/Cntr=0.3,0.1

Type RM Length L Ch R = 1 ,243     ,127.9,116.8,109.9
XS GIS Cut Line= 2
2171447.23457121718820.8379622582171237.37003294718743.633909319
#Sta/Elev= 30
       0 1299.13     8.3  1292.1    11.8 1289.46    20.3 1283.77    24.6 1279.79
    33.1 1270.39    37.4 1266.04    45.7 1252.37   49.071250.933    50.1 1250.65
    58.2 1250.68    67.2 1250.21    71.5 1250.45    73.8 1250.94      80 1252.57
    89.4  1254.2    92.8 1254.59   103.3 1254.85   117.4 1256.37   122.6 1257.22
   129.9 1258.01   173.7 1258.27     178 1258.52   182.8 1259.26     186 1260.04
   189.1 1261.19   195.1    1264   210.9 1273.82   217.1 1277.96   223.6 1281.44
#Mann= 3 ,-1,0
       0      .1       0   49.07    .045       0    73.8      .1       0
Bank Sta=49.07,73.8
XS Rating Curve= 0 ,0
Exp/Cntr(USF)=0,0
Exp/Cntr=0.3,0.1

Type RM Length L Ch R = 1 ,127     ,47.3,55.1,62.9
XS GIS Cut Line= 4
2171467.24768222718779.3097503362171418.54038417718681.398141008
2171318.64072187718694.8174986322171252.53796024718664.996703913
#Sta/Elev= 30
       0 1293.47    11.3 1286.63    24.8 1279.67    30.7  1277.2    42.8 1273.03
    60.5 1267.62    73.9 1261.99    78.5 1259.48    82.8 1256.36    84.4 1255.74
    87.3 1254.96   100.7 1255.92   131.9 1255.44   136.2 1254.96   143.3 1253.33
   156.1    1248   167.8 1247.28   172.3 1247.37   175.3 1247.99   176.3 1248.24
   180.4 1251.25   184.4 1255.83   188.4 1257.38   204.6 1257.87   217.2 1263.67
   252.4 1275.89   256.7 1277.96   269.9 1286.39   274.3 1289.97   282.7 1298.78
#Mann= 3 ,-1,0
       0      .1       0   156.1    .045       0   175.3      .1       0
#XS Ineff= 2 , 0
          104.96 1262.07
Permanent Ineff=
       F       F
Bank Sta=156.1,175.3
XS Rating Curve= 0 ,0
Exp/Cntr(USF)=0,0
Exp/Cntr=0.3,0.1

Type RM Length L Ch R = 1 ,71      ,41.3,40.8,42.5
XS GIS Cut Line= 5
2171481.00862592718784.6662323842171431.06847748718672.102723199
2171347.89525383718628.9184928732171331.04800179718592.977688506
2171255.12516228718575.353196761
#Sta/Elev= 30
       0 1309.27     9.3 1301.29    18.4 1294.44    39.6 1282.27    60.7 1274.24
    69.5 1271.84    78.2 1267.53    97.2 1256.64   100.7 1255.75   164.2 1254.67
   181.6 1254.95   189.5 1253.14  196.751247.374   198.5 1245.97     203 1245.32
   207.5 1245.41     212 1247.45   219.5 1253.92   222.5 1255.37   225.4 1255.96
   253.9 1256.03   256.6  1256.7   259.5 1258.49     280 1278.31   296.5 1287.91
   300.6 1290.91   304.7  1295.7   308.8 1302.33   314.1  1309.7   334.5 1328.85
#Mann= 5 ,-1,0
       0      .1       0  153.14     .06       0  173.14      .1       0
  196.75    .045       0     212      .1       0
Bank Sta=196.75,212
XS Rating Curve= 0 ,0
Exp/Cntr(USF)=0,0
Exp/Cntr=0.3,0.1

Type RM Length L Ch R = 1 ,31      ,13.6,13.6,13.6
XS GIS Cut Line= 5
2171492.69860155 718736.247473032171477.61909459718685.075999696
 2171436.0195523718638.2849156192171337.22532754 718572.76098605
2171262.88411244718555.574765887
#Sta/Elev= 30
       0 1282.48    11.5 1276.51    40.7 1265.97    44.9 1264.12    53.2 1258.09
    58.6 1256.13    63.9 1255.66    90.7 1256.42   161.4 1254.61   168.6 1253.75
   175.9 1252.03   178.2 1251.22  181.391249.217     183 1248.11   187.8 1246.52
   190.3 1246.42   192.6 1246.94  195.681249.128   202.2 1253.43     207 1254.72
   235.6 1255.02   239.7 1255.64   243.8 1258.05   247.9 1261.22   268.4 1280.97
   272.5 1284.23   280.7 1289.79   293.1 1299.32   301.3 1307.45   310.8 1315.57
#Mann= 5 ,-1,0
       0      .1       0   93.35     .06       0  165.96      .1       0
  181.39    .045       0  195.68      .1       0
Bank Sta=181.39,195.68
XS Rating Curve= 0 ,0
Exp/Cntr(USF)=0,0
Exp/Cntr=0.3,0.1

Type RM Length L Ch R = 1 ,17      ,,,
XS GIS Cut Line= 4
2171521.43636514718726.0063754852171516.92934937718693.499625719
2171352.38785438718562.6526348212171255.88160755718542.099797099
#Sta/Elev= 30
       0 1275.58      13  1270.2      17 1267.48    25.1 1260.88    27.6 1259.22
    29.1 1258.26    33.3 1256.91    84.7 1256.85     149 1254.74   171.8 1251.23
   176.9 1249.62   181.1 1247.76   187.6 1245.85   200.4 1245.21   212.7 1245.79
   222.9 1246.28   226.1 1247.08     228 1247.67   233.1 1251.02   238.2 1253.26
   243.3 1254.36   263.7 1255.22   267.8 1257.47   271.9 1261.03   288.2 1277.68
   292.3 1281.22   308.5 1292.88     321    1301   325.1 1304.16   341.7 1318.49
#Mann= 4 ,-1,0
       0      .1       0   92.82     .06       0   187.6    .045       0
   212.7      .1       0
Bank Sta=187.6,212.7
XS Rating Curve= 0 ,0
Exp/Cntr(USF)=0,0
Exp/Cntr=0.3,0.1
LCMann Table=0

Chan Stop Cuts=-1
Use User Specified Reach Order=0
Composite Channel Slope=5